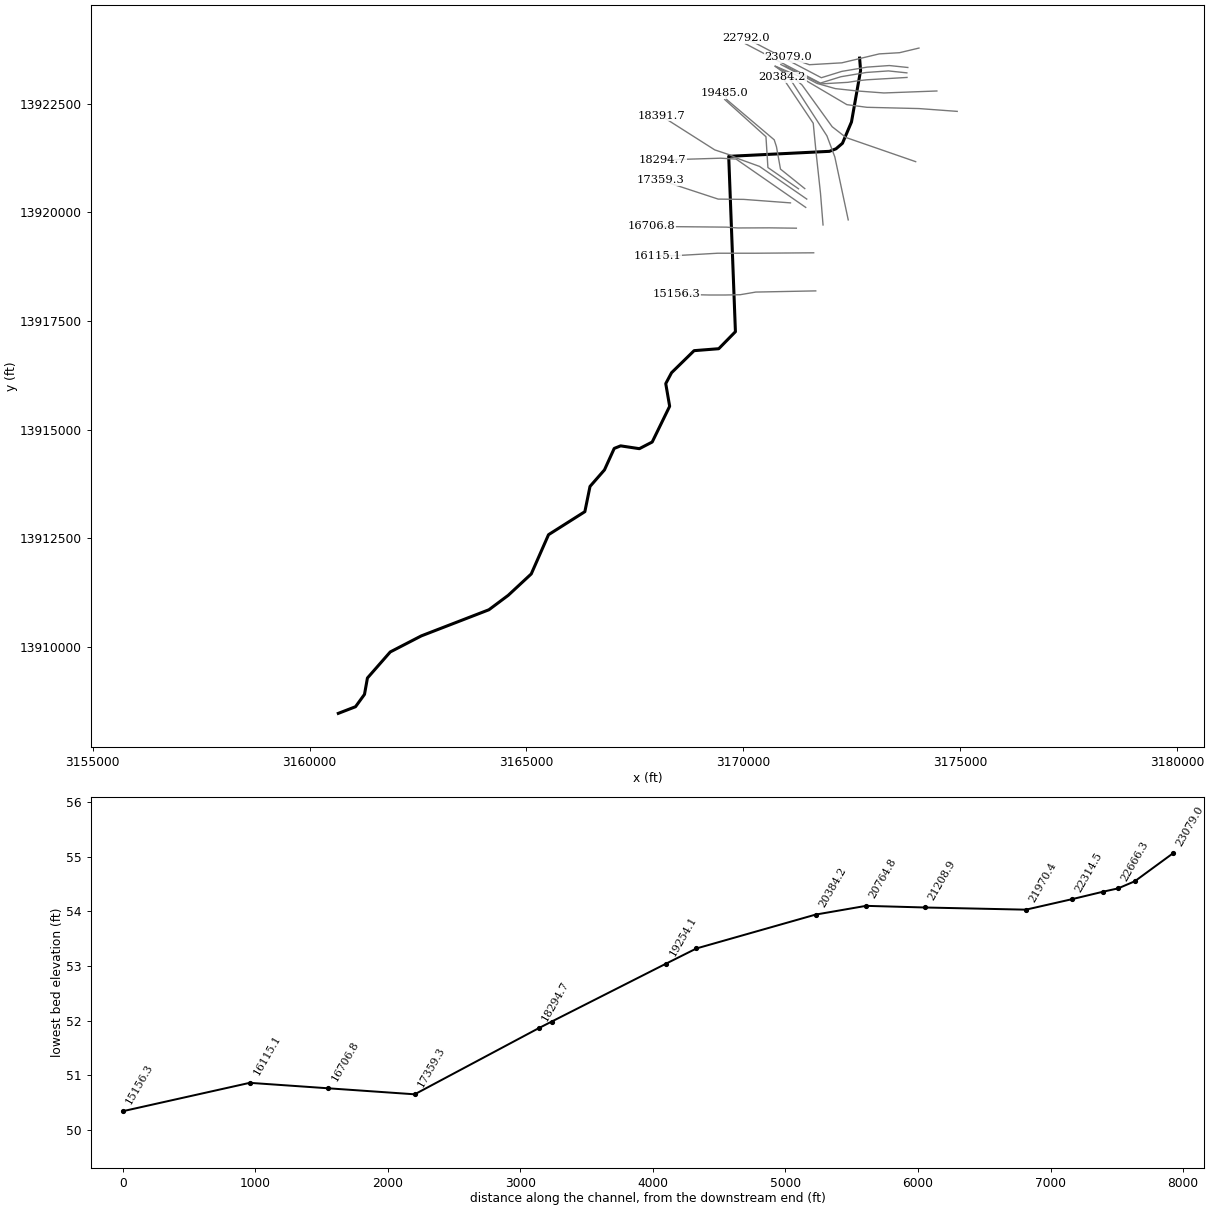
--- P130-02-00.PRJ (project) ---

Proj Title=P130-02-00
Current Plan=p02
Default Exp/Contr=.3,.1
English Units
Geom File=g01
Flow File=f01
Flow File=f02
Plan File=p01
Plan File=p02
Y Axis Title=Elevation
X Axis Title(PF)=Main Channel Distance
X Axis Title(XS)=Station
BEGIN DESCRIPTION:
Greens Bayou Watershed
Williams Gully
HCFCD Unit P130-02-00
Flood Hazard Model
10, 2, 1, 0.2% Event
Filename P130-02-00.prj
Prepared by:  Watershed Concepts  Date:
Reviewed by:                      Date:
STATUS FINAL
END DESCRIPTION:
DSS Export Rating Curves= 0
DSS Export Rating Curve Sorted= 0
DSS Export Volume Flow Curves= 0
DXF OffsetX= 0
DXF OffsetY= 0
DXF ScaleX= 1
DXF ScaleY= 10

--- P130-02-00.p02 (plan) ---

Plan Title=Floodway
Version=Version 3.0.1  Mar 2001
Short Identifier=Floodway0607
Geom File=g01
Flow File=f02
Subcritical Flow
K Sum by GR= 0
Std Step Tol= 0.01
Critical Tol= 0.01
Num of Std Step Trials= 20
Max Error Tol= 0.3
Flow Tol Ratio= 0.001
Split Flow NTrial= 30
Split Flow Tol= 0.02
Split Flow Ratio= 0.02
Log Output Level= 0
Friction Slope Method= 1
Unsteady Friction Slope Method= 2
Parabolic Critical Depth
Global Vel Dist= 0 , 0 , 0
Global Log Level= 0
CheckData=True
Encroach Param=-1 ,0,0, 2
Encroach River=P130-02-00
Encroach Reach=Reach - 1
Encroach Node=23079.0
       1  4945.4    5044
Encroach Node=22792.0
       1  4963.1    5041
Encroach Node=22729.1
       1  4963.1    5041
Encroach Node=22666.3
       1  4963.1    5041
Encroach Node=22554.6
       1  4945.3  5081.1
Encroach Node=22314.5
       1  4896.1    5103
Encroach Node=21970.4
       1  4940.2    5062
Encroach Node=21208.9
       1  4953.8    5058
Encroach Node=20764.8
       1  4953.8    5058
Encroach Node=20384.2
       1  4931.3  5096.6
Encroach Node=19485.0
       1  4940.6  5048.8
Encroach Node=19254.1
       1  4940.6  5048.8
Encroach Node=18391.7
       1  4935.6  5060.3
Encroach Node=18294.7
       1  4935.6  5060.3
Encroach Node=17359.3
       1  4946.9  5061.9
Encroach Node=16706.8
       1    4939  5065.5
Encroach Node=16115.1
       1  4938.9  5065.5
Encroach Node=15156.3
       1  4939.1  5065.6
Encroach Node=14740.4
       1  4933.9  5066.1
Encroach Node=14310.8
       1  4933.2  5083.5
Encroach Node=13794.8
       1  4933.2  5083.5
Encroach Node=13283.4
       1  4933.2  5083.5
Encroach Node=12755.0
       1 4934.65 5065.35
Encroach Node=12098.4
       1 4934.65 5065.35
Encroach Node=11497.0
       1  4937.2  5074.5
Encroach Node=10738.1
       1  4937.2  5074.5
Encroach Node=9999.3
       1  4946.4  5095.7
Encroach Node=8942.4
       1  4935.8  5091.8
Encroach Node=8322.3
       1  4936.5  5081.2
Encroach Node=7857.1
       1  4936.5  5081.2
Encroach Node=7472.3
       1  4931.1  5072.8
Encroach Node=6811.1
       1  4931.1  5072.8
Encroach Node=6251.7
       1  4940.7  5087.8
Encroach Node=5733.1
       1  4940.7  5087.8
Encroach Node=5243.3
       1    4934  5084.6
Encroach Node=4669.9
       1    4934  5084.6
Encroach Node=4113.2
       1    4929  5110.2
Encroach Node=3409.2
       1    4929  5093.1
Encroach Node=2887.5
       1  4925.6  5085.3
Encroach Node=2300.5
       1  4925.6  5085.3
Encroach Node=1773.7
       1  4923.8  5081.4
Encroach Node=1205.3
       1  4923.8  5081.4
Encroach Node=261.2
       1  4929.9  5091.3
Encroach Reach=P130-02-00_0003
Encroach Node=23079.0
       1  4945.4    5044
Encroach Node=22792.0
       1  4963.1    5041
Encroach Node=22729.1
       1  4963.1    5041
Encroach Node=22666.3
       1  4963.1    5041
Encroach Node=22554.6
       1  4945.3  5081.1
Encroach Node=22314.5
       1  4896.1    5103
Encroach Node=21970.4
       1  4940.2    5062
Encroach Node=21208.9
       1  4953.8    5058
Encroach Node=20764.8
       1  4953.8    5058
Encroach Node=20384.2
       1  4931.3  5096.6
Encroach Node=19485.0
       1  4940.6  5048.8
Encroach Node=19254.1
       1  4940.6  5048.8
Encroach Node=18391.7
       1  4935.6  5060.3
Encroach Node=18294.7
       1  4935.6  5060.3
Encroach Node=17359.3
       1  4946.9  5061.9
Encroach Node=16706.8
       1    4939  5065.5
Encroach Node=16115.1
       1  4938.9  5065.5
Encroach Node=15156.3
       1  4939.1  5065.6
Encroach Node=14740.4
       1  4933.9  5066.1
Encroach Node=14310.8
       1  4933.2  5083.5
Encroach Node=13794.8
       1  4933.2  5083.5
Encroach Node=13283.4
       1  4933.2  5083.5
Encroach Node=12755.0
       1 4934.65 5065.35
Encroach Node=12098.4
       1 4934.65 5065.35
Encroach Node=11497.0
       1  4937.2  5074.5
Encroach Node=10738.1
       1  4937.2  5074.5
Encroach Node=9999.3
       1  4946.4  5095.7
Encroach Node=8942.4
       1  4935.8  5091.8
Encroach Node=8322.3
       1  4936.5  5081.2
Encroach Node=7857.1
       1  4936.5  5081.2
Encroach Node=7472.3
       1  4931.1  5072.8
Encroach Node=6811.1
       1  4931.1  5072.8
Encroach Node=6251.7
       1  4940.7  5087.8
Encroach Node=5733.1
       1  4940.7  5087.8
Encroach Node=5243.3
       1    4934  5084.6
Encroach Node=4669.9
       1    4934  5084.6
Encroach Node=4113.2
       1    4929  5110.2
Encroach Node=3409.2
       1    4929  5093.1
Encroach Node=2887.5
       1  4925.6  5085.3
Encroach Node=2300.5
       1  4925.6  5085.3
Encroach Node=1773.7
       1  4923.8  5081.4
Encroach Node=1205.3
       1  4923.8  5081.4
Encroach Node=261.2
       1  4929.9  5091.3
Computation Interval=1HOUR
Output Interval=1HOUR
Run HTab= 0
Run UNet= 0
Run PostProcess= 0
UNET Theta= 1
UNET ZTol= 0.02
UNET ZSATol= 0.1
UNET MxIter= 20
UNET MaxInSteps= 20
UNET DtIC= 0
UNET DtMin= 0
UNET MaxCRTS= 20
UNET WFStab= 2
UNET SFStab= 1
UNET WFX= 1
UNET SFX= 1
UNET Convert EG Bridges=-1
UNET Use Existing IB Tables=-1
Instantaneous Interval=1HOUR
Write IC File= 0
Write Velocity= 0
Write Detailed= 0

--- P130-02-00.p01 (plan) ---

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Plan Title=FEMA Effective June 2007
Short Identifier=FEMAeff0607
Geom File=g01
Flow File=f01
Encroach Param=-1 ,0,0, 0

--- P130-02-00.f02 (steady flow) ---

Flow Title= Floodway
Number of Profiles= 2
Profile Names=1PCT_100yr, 1PCTFloodway_100yrFW
River Rch & RM=P130-02-00,P130-02-00_0003,23079.0
     594     594
River Rch & RM=P130-02-00,P130-02-00_0003,21970.4
     650     650
River Rch & RM=P130-02-00,P130-02-00_0003,20384.2
     693     693
River Rch & RM=P130-02-00,P130-02-00_0003,19254.1
     732     732
River Rch & RM=P130-02-00,P130-02-00_0003,18294.7
     772     772
River Rch & RM=P130-02-00,P130-02-00_0003,17359.3
     829     829
River Rch & RM=P130-02-00,P130-02-00_0003,16115.1
     876     876
River Rch & RM=P130-02-00,P130-02-00_0003,15156.3
     946     946
River Rch & RM=P130-02-00,P130-02-00_0003,13794.8
    1004    1004
River Rch & RM=P130-02-00,P130-02-00_0003,12755
    1078    1078
River Rch & RM=P130-02-00,P130-02-00_0003,11497
    1174    1174
River Rch & RM=P130-02-00,P130-02-00_0003,9999.3
    2662    2662
River Rch & RM=P130-02-00,P130-02-00_0003,8942.4
    2852    2852
River Rch & RM=P130-02-00,P130-02-00_0003,7857.1
    3048    3048
River Rch & RM=P130-02-00,P130-02-00_0003,6811.1
    3247    3247
River Rch & RM=P130-02-00,P130-02-00_0003,5243.3
    3522    3522
River Rch & RM=P130-02-00,P130-02-00_0003,2300.5
    3727    3727
Boundary for River Rch & Prof#=P130-02-00,P130-02-00_0003, 1
Up Type= 0
Dn Type= 3
Dn Slope= 0.00050
Boundary for River Rch & Prof#=P130-02-00,P130-02-00_0003, 2
Up Type= 0
Dn Type= 1
Dn Known WS=51.82

--- P130-02-00.f01 (steady flow) ---

Flow Title= FEMA Effective June 2007
Number of Profiles= 4
Profile Names=10PCT_10yr, 2PCT_50yr, 1PCT_100yr, 0.2PCT_500yr
River Rch & RM=P130-02-00,P130-02-00_0003,23079.0
     328     504     594     863
River Rch & RM=P130-02-00,P130-02-00_0003,21970.4
     359     551     650     945
River Rch & RM=P130-02-00,P130-02-00_0003,20384.2
     383     588     693    1008
River Rch & RM=P130-02-00,P130-02-00_0003,19254.1
     405     621     732    1064
River Rch & RM=P130-02-00,P130-02-00_0003,18294.7
     427     655     772    1122
River Rch & RM=P130-02-00,P130-02-00_0003,17359.3
     458     703     829    1205
River Rch & RM=P130-02-00,P130-02-00_0003,16115.1
     484     743     876    1272
River Rch & RM=P130-02-00,P130-02-00_0003,15156.3
     523     802     946    1375
River Rch & RM=P130-02-00,P130-02-00_0003,13794.8
     555     851    1004    1459
River Rch & RM=P130-02-00,P130-02-00_0003,12755
     596     914    1078    1567
River Rch & RM=P130-02-00,P130-02-00_0003,11497
     649     996    1174    1706
River Rch & RM=P130-02-00,P130-02-00_0003,9999.3
    1489    2265    2662    3838
River Rch & RM=P130-02-00,P130-02-00_0003,8942.4
    1592    2425    2852    4114
River Rch & RM=P130-02-00,P130-02-00_0003,7857.1
    1699    2591    3048    4399
River Rch & RM=P130-02-00,P130-02-00_0003,6811.1
    1807    2759    3247    4690
River Rch & RM=P130-02-00,P130-02-00_0003,5243.3
    1957    2992    3522    5091
River Rch & RM=P130-02-00,P130-02-00_0003,2300.5
    2067    3165    3727    5389
Boundary for River Rch & Prof#=P130-02-00,P130-02-00_0003, 1
Up Type= 0
Dn Type= 3
Dn Slope= 0.00050
Boundary for River Rch & Prof#=P130-02-00,P130-02-00_0003, 2
Up Type= 0
Dn Type= 3
Dn Slope= 0.00050
Boundary for River Rch & Prof#=P130-02-00,P130-02-00_0003, 3
Up Type= 0
Dn Type= 3
Dn Slope= 0.00050
Boundary for River Rch & Prof#=P130-02-00,P130-02-00_0003, 4
Up Type= 0
Dn Type= 3
Dn Slope= 0.00050

--- P130-02-00.g01 (geometry) ---

Geom Title=P130-02-00 June 2007
Version=Version 3.0.1  Mar 2001

River Reach=P130-02-00      ,P130-02-00_0003
Reach XY= 30
      3172682.83     13923553.86      3172705.25       13923268.
      3172495.25       13922082.      3172287.25       13921592.
      3172138.75       13921465.      3171986.95     13921406.34
      3169664.75       13921291.       3169819.5       13917253.
      3169435.25       13916861.        3168867.       13916816.
        3168347.       13916308.      3168213.25       13916057.
      3168303.25       13915535.        3167901.       13914712.
      3167604.83     13914558.65       3167173.3     13914623.48
      3167025.41     13914564.72      3166800.25       13914070.
        3166467.       13913689.      3166348.25       13913108.
      3165510.75       13912578.      3165112.25       13911674.
        3164581.       13911181.       3164136.5       13910849.
       3162577.5       13910247.      3161861.25       13909877.
       3161335.5       13909277.      3161267.68     13908900.19
        3161061.       13908616.      3160663.95     13908462.58

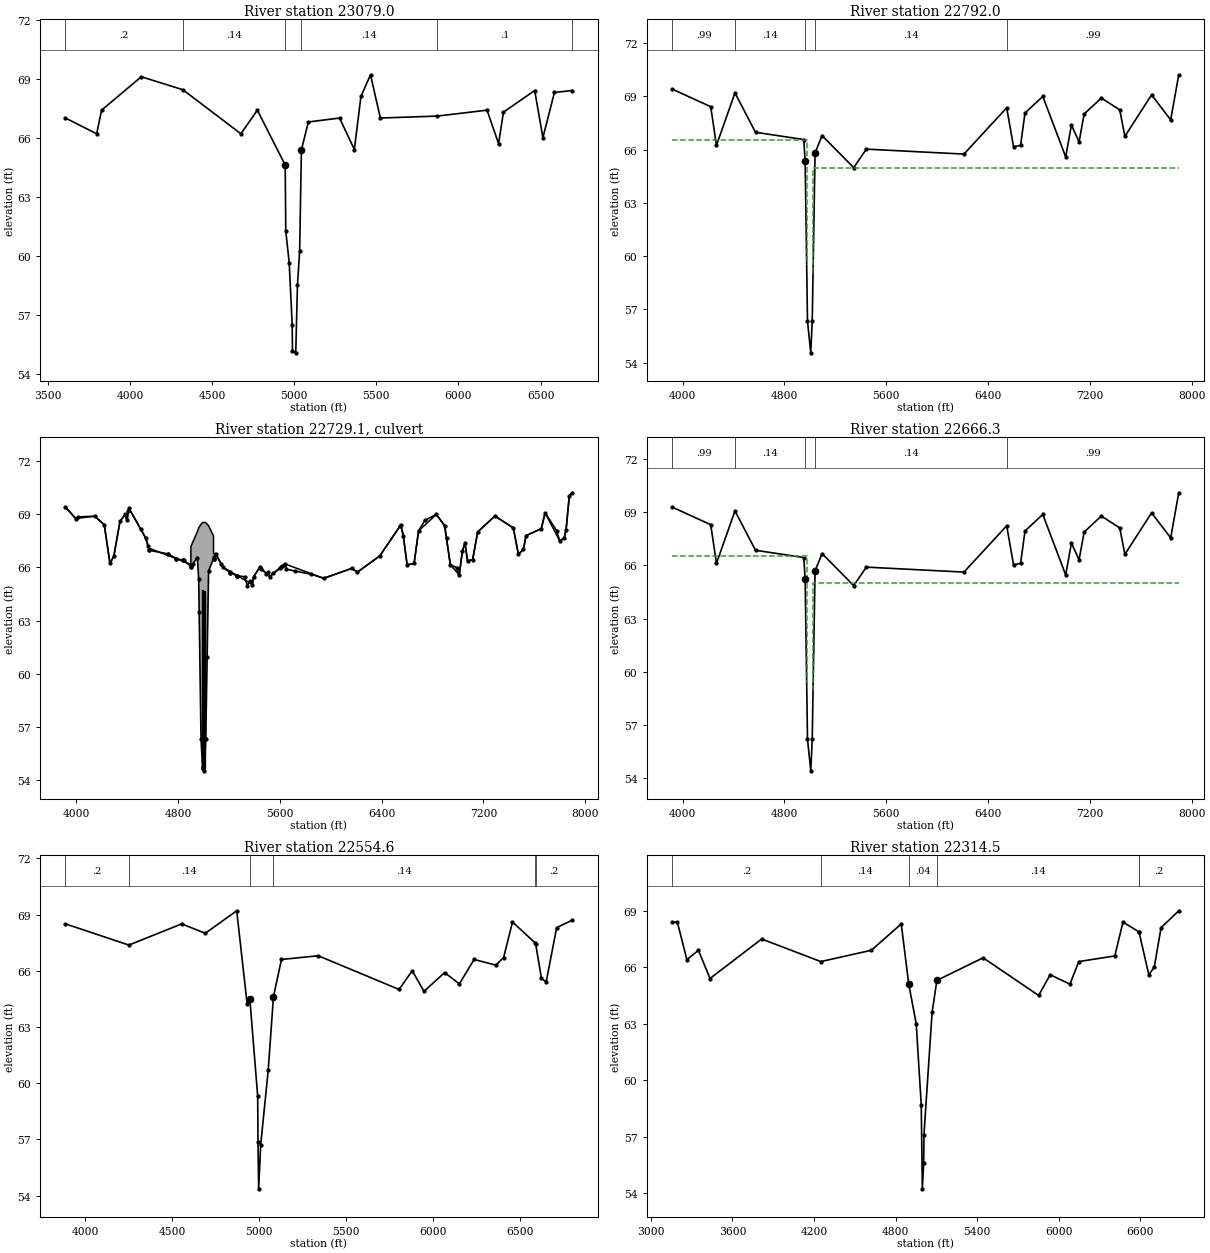
Type RM Length L Ch R = 1 ,23079.0 ,291.5,287.05,271.2
BEGIN DESCRIPTION:
Cross Section 23079.0
END DESCRIPTION:
XS GIS Cut Line= 6
      3174051.41     13923784.92      3173602.22     13923677.94
      3173136.77     13923650.77      3172272.51     13923444.74
      3171524.29     13923401.29      3171035.68     13923575.62
#Sta/Elev= 30
  3607.8      67  3797.8    66.2  3827.8    67.4  4069.6    69.1  4322.4   68.44
  4675.8    66.2  4775.8    67.4  4945.4   64.61  4948.9   61.25  4969.7   59.65
    4988    56.5  4989.7   55.16  5009.6   55.06  5019.9    58.5  5033.4   60.25
    5044   65.38  5086.3    66.8  5276.3      67  5366.3    65.4  5406.3    68.1
  5464.6    69.2  5524.6      67  5870.6    67.1    6174    67.4    6244    65.7
    6274    67.3    6464    68.4    6514      66    6584    68.3  6692.8    68.4
#Mann= 6 , 1 , 0
  3607.8      .2       0  4322.4     .14       0  4945.4     .04       0
    5044     .14       0  5870.6      .1       0  6692.8      .2       0
Bank Sta=4945.4,5044
XS Rating Curve= 0
Exp/Cntr=.5,.3

Type RM Length L Ch R = 1 ,22792.0 ,125.7,125.7,125.7
BEGIN DESCRIPTION:
Upstream Section of Bridge/Culvert/Weir
END DESCRIPTION:
XS GIS Cut Line= 6
      3173794.82     13923337.37      3173368.42     13923382.39
      3172859.45     13923346.48      3172273.64     13923248.22
      3171800.52     13923101.81      3170070.86     13924008.91
#Sta/Elev= 30
    3916   69.42    4221   68.42    4266   66.24  4411.5    69.2  4572.9   66.98
  4952.3   66.57  4963.1   65.34  4981.5   56.34  5007.2   54.55  5018.6   56.32
    5041   65.82  5096.2   66.79  5344.4   64.99  5444.4   66.03  6210.9   65.75
  6546.9   68.36  6600.9   66.16  6655.9   66.24  6690.9   68.07  6830.6      69
  7010.6   65.59  7055.6   67.39  7115.6   66.44  7155.6   68.01  7290.6   68.91
  7435.6   68.24  7475.6   66.75  7685.6   69.09  7835.6   67.68    7899   70.22
#Mann= 5 , 1 , 0
    3916     .99       0  4411.5     .14       0  4963.1     .04       0
    5041     .14       0  6546.9     .99       0
#XS Ineff= 2 , 0
       0    4975   66.55    5025       0   64.98
Permanent Ineff=
       F       F
Bank Sta=4963.1,5041
XS Rating Curve= 0
Exp/Cntr=.5,.3

Type RM Length L Ch R = 2 ,22729.1 ,,,
BEGIN DESCRIPTION:
WILL CLAYTON
Structure ID: P32-2
END DESCRIPTION:
Bridge Culvert--1,0,-1,-1, 0
Deck Dist Width WeirC Skew NumUp NumDn MinLoCord MaxHiCord MaxSubmerge Is_Ogee
10,105.7,3,0, 60, 60, , , .95, 0, 1,1,,
    3916    3996    4146    4221    4266    4296  4344.8  4384.8  4399.8  4414.8
  4547.9  4572.9 4901.49  4901.6  4952.3  4963.1  4981.5  4993.5  5007.2  5018.6
    5041  5079.7 5079.81  5096.2  5153.8  5384.4  5394.4  5444.4    5520    5645
  5945.9  6165.9  6210.9  6385.9  6550.9  6570.9  6600.9  6655.9  6690.9  6830.6
  6895.6  6940.6  7010.6  7035.6  7055.6  7075.6  7115.6  7155.6  7290.6  7435.6
  7475.6  7515.6  7535.6  7655.6  7685.6  7800.6  7835.6  7850.6  7875.6    7899
    69.4   68.75   68.88    68.4   66.22   66.62   68.59   68.98   68.64   69.33
   67.63   67.08   66.17   67.17      68   68.22   68.42   68.52   68.53   68.52
   68.34   67.77   66.77   66.78   66.01   65.03   65.47   66.02   65.48   66.18
   65.38   65.94   65.73   66.64   68.38   67.79   66.14   66.22   68.05   68.98
   68.35   66.15   65.57   66.92   67.37   66.37   66.42   67.99   68.89   68.22
   66.73   67.02   67.78   68.18   69.07   67.48   67.66   68.13   70.04    70.2
    69.4   68.75   68.88    68.4   66.22   66.62   68.59   68.98   68.64   69.33
   67.63   66.96   66.05   66.05   66.55   65.32   56.32   54.71   54.53    56.3
    65.8   66.48   66.48   66.77      66      65   65.46   66.01   65.47   66.17
   65.38   65.94   65.73   66.64   68.38   67.79   66.14   66.22   68.05   68.98
   68.35   66.15   65.57   66.92   67.37   66.37   66.42   67.99   68.89   68.22
   66.73   67.02   67.78   68.18   69.07   67.48   67.66   68.13   70.04    70.2
    3916    3996    4146    4221    4266    4296  4344.8  4384.8  4399.8  4414.8
  4547.9  4572.9 4901.49  4901.6  4952.3  4963.1  4981.5  4993.5  5007.2  5018.6
    5041  5079.7 5079.81  5096.2  5153.8  5384.4  5394.4  5444.4    5520    5645
  5945.9  6165.9  6210.9  6385.9  6550.9  6570.9  6600.9  6655.9  6690.9  6830.6
  6895.6  6940.6  7010.6  7035.6  7055.6  7075.6  7115.6  7155.6  7290.6  7435.6
  7475.6  7515.6  7535.6  7655.6  7685.6  7800.6  7835.6  7850.6  7875.6    7899
    69.4   68.75   68.88    68.4   66.22   66.62   68.59   68.98   68.64   69.33
   67.63   67.08   66.17   67.17      68   68.22   68.42   68.52   68.53   68.52
   68.34   67.77   66.77   66.78   66.01   65.03   65.47   66.02   65.48   66.18
   65.38   65.94   65.73   66.64   68.38   67.79   66.14   66.22   68.05   68.98
   68.35   66.15   65.57   66.92   67.37   66.37   66.42   67.99   68.89   68.22
   66.73   67.02   67.78   68.18   69.07   67.48   67.66   68.13   70.04    70.2
    69.3   68.65   68.78    68.3   66.12   66.52   68.49   68.88   68.54   69.23
   67.53   66.86   65.95   65.95   66.45   65.22   56.22   54.61   54.43    56.2
    65.7   66.38   66.38   66.67    65.9    64.9   65.36   65.91   65.37   66.07
   65.28   65.84   65.63   66.54   68.28   67.69   66.04   66.12   67.95   68.88
   68.25   66.05   65.47   66.82   67.27   66.27   66.32   67.89   68.79   68.12
   66.63   66.92   67.68   68.08   68.97   67.38   67.56   68.03   69.94    70.1
BR Coef= 1 , 0 , 0 ,1.25, 0 ,,,.8,-1,2,0,
WSPro=,,,, 1 ,,,, 0 ,,,, 0 ,,,,-1 ,-1 ,-1 , 0 , 0 , 0 , 0 , 0
Culvert=2,10,12,105.7,.015,.4,1,8,1,54.71,4993.6,54.61,4993.6,Culvert #1  , 0 ,10
Culvert Bottom n=.015
Culvert=2,10,12,105.7,.015,.4,1,8,1,54.68,5007,54.61,5007,Culvert #2  , 0 ,10
Culvert Bottom n=.015
BR U #Sta/Elev= 109
    3916    69.4    3996   68.75    4016   68.84    4146   68.88    4221    68.4
    4266   66.22    4296   66.62  4344.8   68.59  4384.8   68.98  4399.8   68.64
  4411.5   69.18  4414.8   69.33  4507.9   68.16  4547.9   67.63  4563.8    67.2
  4572.9   66.96  4573.8   66.96  4724.9   66.75  4725.3   66.75  4785.9   66.49
  4788.1   66.48  4838.5    66.4  4841.3    66.4    4845   66.39 4901.49   66.05
  4901.6   66.05 4901.71   66.04  4902.5   66.04  4917.8    66.2  4952.3   66.55
  4963.1   65.32  4966.9   63.46  4981.5   56.32  4993.5   54.71  4995.3   54.69
 4995.69   54.68  4995.8   54.68 4995.91   54.68  5007.2   54.53  5018.6    56.3
  5029.6   60.97    5041    65.8 5079.59   66.48  5079.7   66.48 5079.81   66.48
  5086.4    66.6  5096.2   66.77  5141.6   66.16  5153.8      66  5207.7   65.71
  5210.8    65.7  5211.5    65.7  5263.5   65.52  5263.7   65.52  5263.8   65.52
  5324.4   65.47  5344.4   64.97  5369.4   65.23  5384.4      65  5394.4   65.46
  5444.4   66.01    5450   65.93    5495   65.64    5510   65.75    5520   65.47
  5549.7   65.66    5600   65.97  5609.7   66.01  5619.7   66.06  5633.4   66.12
    5645   66.17  5652.1   65.89  5721.2   65.79  5847.1   65.61  5945.9   65.38
  6165.9   65.94  6210.9   65.73  6385.9   66.64  6546.9   68.34  6550.9   68.38
  6570.9   67.79  6600.9   66.14  6655.9   66.22  6690.9   68.05  6740.6   68.64
  6830.6   68.98  6895.6   68.35  6910.6   67.64  6940.6   66.15  6990.6   65.98
  7010.6   65.57  7035.6   66.92  7055.6   67.37  7075.6   66.37  7115.6   66.42
  7155.6   67.99  7290.6   68.89  7435.6   68.22  7475.6   66.73  7515.6   67.02
  7535.6   67.78  7655.6   68.18  7685.6   69.07  7775.6   68.07  7800.6   67.48
  7835.6   67.66  7850.6   68.13  7875.6   70.04    7899    70.2
BR U #Mann= 5
    3916     .99  4411.5     .14  4963.1     .04    5041     .14  6546.9     .99
BR U Banks=4963.1,5041
BR D #Sta/Elev= 109
    3916    69.3    3996   68.65    4016   68.74    4146   68.78    4221    68.3
    4266   66.12    4296   66.52  4344.8   68.49  4384.8   68.88  4399.8   68.54
  4411.5   69.08  4414.8   69.23  4507.9   68.06  4547.9   67.53  4563.8    67.1
  4572.9   66.86  4573.8   66.86  4724.9   66.65  4725.3   66.65  4785.9   66.39
  4788.1   66.38  4838.5    66.3  4841.3    66.3    4845   66.29 4901.49   65.95
  4901.6   65.95 4901.71   65.94  4902.5   65.94  4917.8    66.1  4952.3   66.45
  4963.1   65.22  4966.9   63.36  4981.5   56.22  4993.5   54.61  4995.3   54.59
 4995.69   54.58  4995.8   54.58 4995.91   54.58  5007.2   54.43  5018.6    56.2
  5029.6   60.87    5041    65.7 5079.59   66.38  5079.7   66.38 5079.81   66.38
  5086.4    66.5  5096.2   66.67  5141.6   66.06  5153.8    65.9  5207.7   65.61
  5210.8    65.6  5211.5    65.6  5263.5   65.42  5263.7   65.42  5263.8   65.42
  5324.4   65.37  5344.4   64.87  5369.4   65.13  5384.4    64.9  5394.4   65.36
  5444.4   65.91    5450   65.83    5495   65.54    5510   65.65    5520   65.37
  5549.7   65.56    5600   65.87  5609.7   65.91  5619.7   65.96  5633.4   66.02
    5645   66.07  5652.1   65.79  5721.2   65.69  5847.1   65.51  5945.9   65.28
  6165.9   65.84  6210.9   65.63  6385.9   66.54  6546.9   68.24  6550.9   68.28
  6570.9   67.69  6600.9   66.04  6655.9   66.12  6690.9   67.95  6740.6   68.54
  6830.6   68.88  6895.6   68.25  6910.6   67.54  6940.6   66.05  6990.6   65.88
  7010.6   65.47  7035.6   66.82  7055.6   67.27  7075.6   66.27  7115.6   66.32
  7155.6   67.89  7290.6   68.79  7435.6   68.12  7475.6   66.63  7515.6   66.92
  7535.6   67.68  7655.6   68.08  7685.6   68.97  7775.6   67.97  7800.6   67.38
  7835.6   67.56  7850.6   68.03  7875.6   69.94    7899    70.1
BR D #Mann= 5
    3916     .99  4411.5     .14  4963.1     .04    5041     .14  6546.9     .99
BR D Banks=4963.1,5041
BC Design=,, 0 ,, 0 ,,,,,,

Type RM Length L Ch R = 1 ,22666.3 ,111.65,111.65,111.65
BEGIN DESCRIPTION:
Downstream Section of Bridge/Culvert/Weir
END DESCRIPTION:
XS GIS Cut Line= 6
      3173772.34     13923213.69      3173345.94     13923258.71
      3172836.97      13923222.8      3172251.16     13923124.54
      3171778.04     13922978.13      3170048.37     13923885.24
#Sta/Elev= 30
    3916   69.29    4221   68.29    4266   66.11  4411.5   69.07  4572.9   66.85
  4952.3   66.44  4963.1   65.21  4981.5   56.21  5007.2   54.42  5018.6   56.19
    5041   65.69  5096.2   66.66  5344.4   64.86  5444.4    65.9  6210.9   65.62
  6546.9   68.23  6600.9   66.03  6655.9   66.11  6690.9   67.94  6830.6   68.87
  7010.6   65.46  7055.6   67.26  7115.6   66.31  7155.6   67.88  7290.6   68.78
  7435.6   68.11  7475.6   66.62  7685.6   68.96  7835.6   67.55    7899   70.09
#Mann= 5 , 1 , 0
    3916     .99       0  4411.5     .14       0  4963.1     .04       0
    5041     .14       0  6546.9     .99       0
#XS Ineff= 2 , 0
       0    4975   66.55    5025       0   64.98
Permanent Ineff=
       F       F
Bank Sta=4963.1,5041
XS Rating Curve= 0
Exp/Cntr=.5,.3

Type RM Length L Ch R = 1 ,22554.6 ,249.1,240.1,224.6
BEGIN DESCRIPTION:
Cross Section 22554.6-Interpolated
END DESCRIPTION:
XS GIS Cut Line= 6
      3173775.56     13923108.27      3172852.91      13923054.4
      3172658.27     13923033.62      3172412.61     13922995.82
      3171791.21     13922959.65      3170965.13     13923373.56
#Sta/Elev= 30
  3884.9    68.5  4249.7   67.37  4553.2    68.5  4689.4      68  4869.9    69.2
  4930.2    64.2  4945.3    64.5  4990.6    59.3  4992.3   56.85  4996.2   54.36
  5007.8   56.71  5051.2    60.7  5081.1    64.6  5127.1    66.6  5338.6    66.8
  5803.8      65  5879.2      66    5947    64.9  6065.7    65.9  6150.5    65.3
  6235.3    66.6    6360    66.3  6404.8    66.7    6456    68.6    6586   67.49
    6589   67.44  6622.5    65.6  6649.7    65.4    6710    68.3  6799.9    68.7
#Mann= 6 , 1 , 0
  3884.9      .2       0  4249.7     .14       0  4945.3     .04       0
  5081.1     .14       0    6586      .1       0    6589      .2       0
Bank Sta=4945.3,5081.1
XS Rating Curve= 0
Exp/Cntr=.3,.1

Type RM Length L Ch R = 1 ,22314.5 ,351.9,344.1,342.2
BEGIN DESCRIPTION:
Cross Section 22314.5-Interpolated
END DESCRIPTION:
XS GIS Cut Line= 6
      3174463.89     13922796.38       3173243.5     13922750.84
      3172633.31     13922796.38      3172123.29     13922851.02
      3171704.35     13922969.42      3170866.47     13923406.57
#Sta/Elev= 30
  3154.9    68.4  3194.9    68.4  3264.9    66.4  3349.9    66.9  3434.9    65.4
  3814.9    67.5  4249.7    66.3  4621.1    66.9  4841.1    68.3  4896.1    65.1
  4951.1      63    4988    58.7  4996.2   54.22  5006.1   55.62    5008    57.1
    5068    63.6    5103    65.3    5443    66.5    5851    64.5  5936.3    65.6
  6081.3    65.1  6146.3    66.3  6411.3    66.6  6471.3    68.4    6586   67.89
    6589   67.88  6661.3    65.6  6701.3      66  6751.3    68.1  6881.4      69
#Mann= 6 , 1 , 0
  3154.9      .2       0  4249.7     .14       0  4896.1     .04       0
    5103     .14       0    6586      .1       0    6589      .2       0
Bank Sta=4896.1,5103
XS Rating Curve= 0
Exp/Cntr=.3,.1

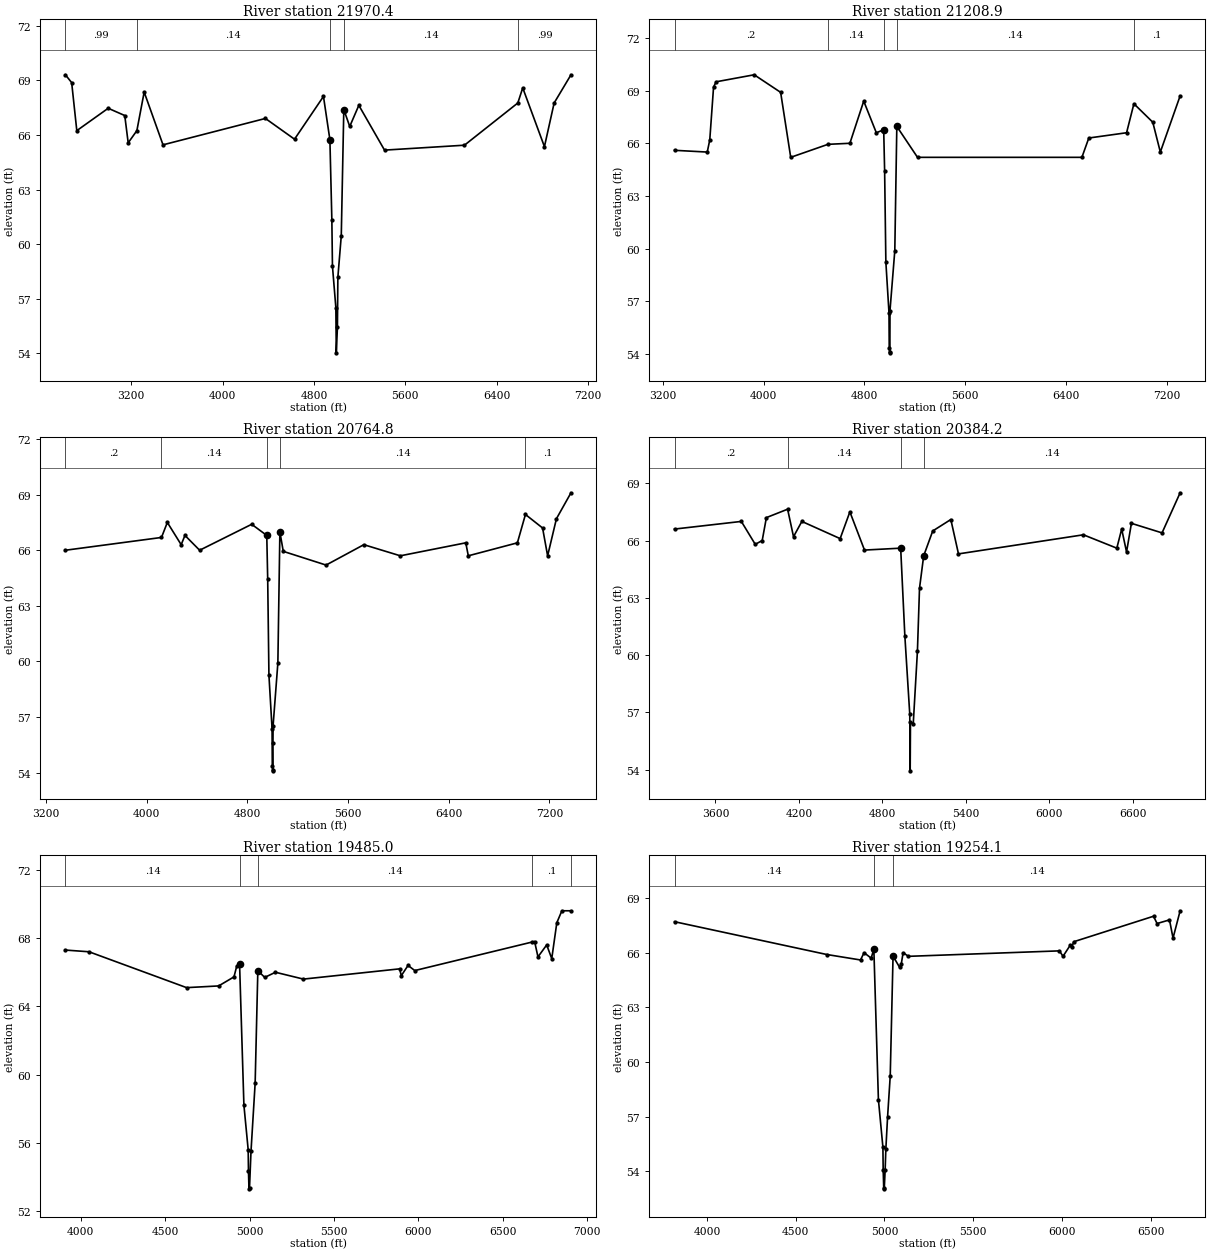
Type RM Length L Ch R = 1 ,21970.4 ,775.4,761.5,726.2
BEGIN DESCRIPTION:
Cross Section 21970.4
END DESCRIPTION:
XS GIS Cut Line= 6
      3174932.86     13922326.75      3174053.42     13922391.39
      3172850.34     13922420.59      3172389.59     13922481.57
      3171273.29     13923138.95      3170737.97     13923368.96
#Sta/Elev= 30
  2623.6   69.31  2678.6   68.88  2723.6   66.24  2998.6   67.47  3143.6   67.07
  3173.6   65.57  3249.7   66.24  3313.6   68.36  3478.6   65.46  4375.4   66.91
  4630.4   65.77  4883.9   68.12  4940.2   65.74  4957.3   61.35  4962.5    58.8
  4992.3   56.52  4996.2   54.03  5006.1   55.43    5010   58.18  5039.8   60.46
    5062    67.4  5113.9   66.47  5193.6   67.63  5418.6   65.17  6118.6   65.44
    6586   67.76  6629.1   68.59  6819.1   65.36  6904.1   67.76  7051.7   69.31
#Mann= 5 , 1 , 0
  2623.6     .99       0  3249.7     .14       0  4940.2     .04       0
    5062     .14       0    6586     .99       0
Bank Sta=4940.2,5062
XS Rating Curve= 0
Exp/Cntr=.3,.1

Type RM Length L Ch R = 1 ,21208.9 ,474.7,444.1,400.4
BEGIN DESCRIPTION:
Cross Section 21208.9-Interpolated
END DESCRIPTION:
XS GIS Cut Line= 6
      3173975.31     13921168.75       3172370.4     13921723.98
      3172050.22     13921973.01       3171356.5     13922933.56
      3171071.89     13923182.59      3170767.68     13923349.98
#Sta/Elev= 30
  3292.4    65.6  3552.4    65.5  3572.4    66.2  3602.4    69.2  3622.4    69.5
  3925.2    69.9  4135.2    68.9  4215.2    65.2  4510.9   65.94  4685.2      66
  4795.2    68.4  4895.2    66.6  4953.8   66.77  4961.2   64.41    4971   59.23
  4995.9   56.34  4997.7   54.33  5000.4   54.07  5002.8   54.14  5003.8   56.48
    5042   59.89    5058   66.96  5222.4    65.2    6528    65.2  6582.9    66.3
  6882.9    66.6  6941.1   68.25    7091    67.2    7151    65.5  7308.3    68.7
#Mann= 5 , 1 , 0
  3292.4      .2       0  4510.9     .14       0  4953.8     .04       0
    5058     .14       0  6941.1      .1       0
Bank Sta=4953.8,5058
XS Rating Curve= 0
Exp/Cntr=.3,.1

Type RM Length L Ch R = 1 ,20764.8 ,386.3,380.6,363.4
BEGIN DESCRIPTION:
Cross Section 20764.8
END DESCRIPTION:
XS GIS Cut Line= 6
      3172420.52     13919827.87      3172111.79      13921275.5
      3171928.84     13921763.35      3171053.03     13923115.15
      3171015.57     13923161.41      3170735.48     13923363.99
#Sta/Elev= 30
  3353.8      66  4117.4   66.69  4163.8    67.5  4273.8    66.3  4303.8    66.8
  4420.5      66    4834    67.4  4953.8    66.8  4961.2   64.44    4971   59.26
  4995.9   56.37  4997.7   54.36  5000.4    54.1  5002.8   54.17  5003.1    55.6
  5003.8   56.51    5042   59.92    5058   66.99  5084.9   65.94    5425    65.2
    5725    66.3    6015    65.7    6535    66.4    6555    65.7    6945    66.4
    7009   67.93  7145.2    67.2  7185.2    65.7  7255.2    67.7  7370.9    69.1
#Mann= 5 , 1 , 0
  3353.8      .2       0  4117.4     .14       0  4953.8     .04       0
    5058     .14       0    7009      .1       0
Bank Sta=4953.8,5058
XS Rating Curve= 0
Exp/Cntr=.3,.1

Type RM Length L Ch R = 1 ,20384.2 ,900.2,899.2,897.4
BEGIN DESCRIPTION:
Cross Section 20384.2-Interpolated
END DESCRIPTION:
XS GIS Cut Line= 5
      3171839.59     13919710.96      3171781.53     13920433.51
      3171678.31     13921388.31       3171613.8     13922052.79
      3170901.05     13923115.88
#Sta/Elev= 30
  3306.4    66.6  3786.4      67  3886.4    65.8  3936.4      66  3966.4    67.2
  4118.9   67.64  4161.3    66.2  4221.3      67  4496.3    66.1  4566.3    67.5
  4671.3    65.5  4931.3    65.6  4961.3      61  4996.6    56.9  4999.6   53.94
  5001.6    56.5  5021.6    56.4  5051.6    60.2  5066.6    63.5  5096.6    65.2
  5161.6    66.5  5291.6    67.1  5346.6    65.3  6244.2    66.3  6484.2    65.6
  6519.2    66.6  6554.2    65.4  6589.2    66.9  6809.2    66.4  6939.2    68.5
#Mann= 4 , 1 , 0
  3306.4      .2       0  4118.9     .14       0  4931.3     .04       0
  5096.6     .14       0
Bank Sta=4931.3,5096.6
XS Rating Curve= 0
Exp/Cntr=.3,.1

Type RM Length L Ch R = 1 ,19485.0 ,232.4,230.9,227.4
BEGIN DESCRIPTION:
Cross Section 19485.0
END DESCRIPTION:
XS GIS Cut Line= 6
      3171418.54     13920548.16      3170858.28     13920997.69
      3170765.63     13921514.18       3170714.1     13921671.79
      3169620.89     13922596.19      3169576.67     13922743.79
#Sta/Elev= 30
  3908.3    67.3  4048.3    67.2  4626.6    65.1  4816.6    65.2  4907.5   65.73
  4923.8   66.36  4940.6   66.48  4966.3   58.22  4991.7    55.6  4993.2   54.38
  4996.4   53.32  4999.6   53.39  5008.3   55.51  5032.9   59.51  5048.8   66.09
  5089.8    65.7  5153.2      66    5319    65.6    5889    66.2    5899    65.8
    5939    66.4    5979    66.1  6674.4   67.77    6689    67.8    6709    66.9
  6760.7    67.6  6790.7    66.8  6820.7    68.9  6850.7    69.6  6904.7    69.6
#Mann= 5 , 1 , 0
  3908.3     .14       0  4940.6     .04       0  5048.8     .14       0
  6674.4      .1       0  6904.7      .2       0
Bank Sta=4940.6,5048.8
XS Rating Curve= 0
Exp/Cntr=.3,.1

Type RM Length L Ch R = 1 ,19254.1 ,806.1,862.4,969.1
BEGIN DESCRIPTION:
Cross Section 19254.1-Interpolated
END DESCRIPTION:
XS GIS Cut Line= 4
      3171273.72     13920544.28      3170568.68     13921033.48
      3170523.52     13921743.13      3169572.44     13922599.74
#Sta/Elev= 30
  3817.4    67.7  4675.5    65.9  4865.5    65.6  4885.5      66  4925.5    65.7
  4940.6    66.2  4966.3   57.94  4991.7   55.32  4993.2    54.1  4996.4   53.04
  4999.6   53.11  5004.3   54.09  5008.3   55.23    5018   56.99  5032.9   59.23
  5048.8   65.81  5085.5    65.2  5095.5    65.4  5105.5      66  5135.5    65.8
  5986.6    66.1  6006.6    65.8  6046.6    66.4  6056.6    66.3  6066.6    66.6
  6516.6      68  6536.6    67.6  6606.6    67.8  6626.6    66.8  6666.6    68.3
#Mann= 3 , 1 , 0
  3817.4     .14       0  4940.6     .04       0  5048.8     .14       0
Bank Sta=4940.6,5048.8
XS Rating Curve= 0
Exp/Cntr=.3,.1

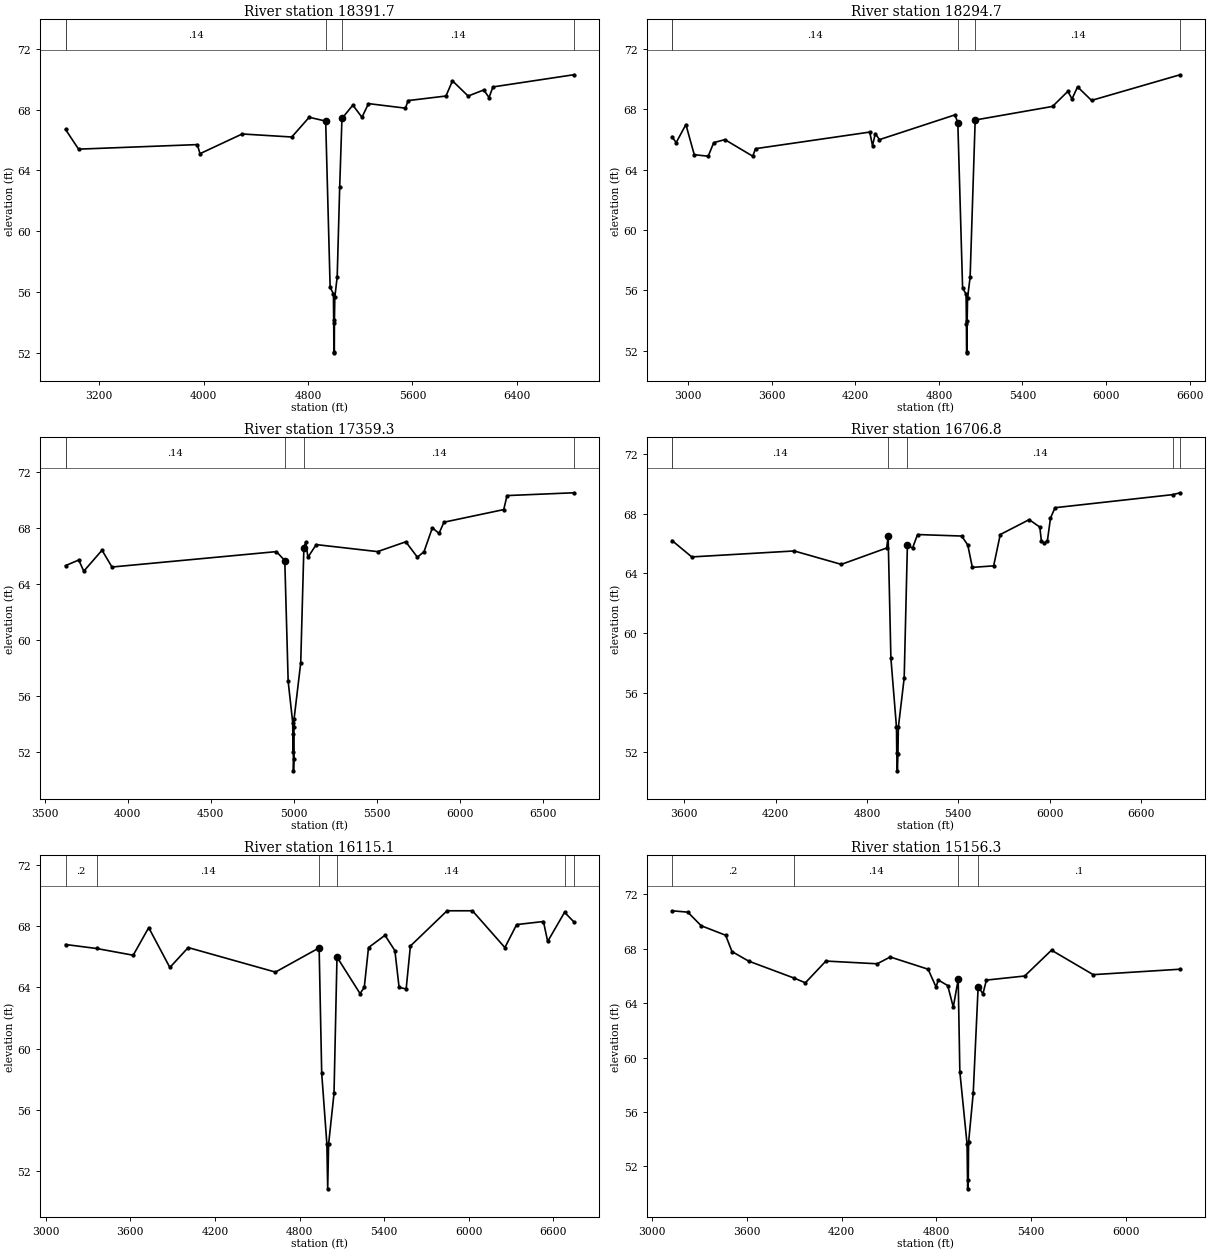
Type RM Length L Ch R = 1 ,18391.7 ,74,97,104.8
BEGIN DESCRIPTION:
Cross Section 18391.7-Interpolated
END DESCRIPTION:
XS GIS Cut Line= 6
      3171464.05     13920307.12      3170375.14     13921059.29
      3169864.41     13921244.48      3169697.09     13921321.94
      3169342.93     13921439.92      3168104.28     13922226.98
#Sta/Elev= 30
  2942.6    66.7  3042.6    65.4  3952.6    65.7  3972.6    65.1    4296    66.4
    4676    66.2  4809.3    67.5  4935.6   67.25  4969.9   56.29  4994.9   55.87
  4997.3   53.92  4998.6   52.06  5001.9   51.98  5002.7   54.12  5005.7   55.64
  5023.9   56.99    5043   62.89  5060.3   67.42  5143.7    68.3  5213.7    67.5
  5263.7    68.4    5547    68.1    5567    68.6    5857    68.9    5907    69.9
    6027    68.9    6147    69.3    6187    68.8    6217    69.5  6834.5    70.3
#Mann= 5 , 1 , 0
  2942.6      .2       0  2942.6     .14       0  4935.6     .04       0
  5060.3     .14       0  6834.5      .2       0
Bank Sta=4935.6,5060.3
XS Rating Curve= 0
Exp/Cntr=.3,.1

Type RM Length L Ch R = 1 ,18294.7 ,933.2,935.4,938.5
BEGIN DESCRIPTION:
Cross Section 18294.7
END DESCRIPTION:
XS GIS Cut Line= 4
       3171440.1     13920115.51      3169835.15     13921228.07
      3169476.04     13921248.39      3168141.23     13921207.74
#Sta/Elev= 30
  2883.1    66.2  2913.1    65.8  2983.1      67  3043.1      65  3143.1    64.9
  3183.1    65.8  3263.1      66  3463.1    64.9  3483.1    65.4  4303.1    66.5
  4323.1    65.6  4343.1    66.4  4373.1      66  4914.7   67.64  4935.6   67.13
  4969.9   56.17  4994.9   55.75  4997.3    53.8  4998.6   51.94  5001.9   51.86
  5002.7      54  5005.7   55.52  5023.9   56.87  5060.3    67.3  5615.6    68.2
  5725.6    69.2  5755.6    68.7  5795.6    69.5  5895.6    68.6  6531.1    70.3
#Mann= 5 , 1 , 0
  2883.1      .2       0  2883.1     .14       0  4935.6     .04       0
  5060.3     .14       0  6531.1      .2       0
Bank Sta=4935.6,5060.3
XS Rating Curve= 0
Exp/Cntr=.3,.1

Type RM Length L Ch R = 1 ,17359.3 ,650.4,652.5,643.9
BEGIN DESCRIPTION:
Cross Section 17359.3
END DESCRIPTION:
XS GIS Cut Line= 4
      3171088.81      13920219.3      3170011.32      13920299.8
      3169421.84     13920306.57      3168100.58     13920740.22
#Sta/Elev= 30
  3625.9    65.3  3705.9    65.7  3735.9    64.9  3845.9    66.4  3905.9    65.2
  4896.4    66.3  4946.9   65.66  4967.3   57.03  4994.6    54.1  4996.7   51.98
  4997.7   53.25  4999.3   50.65  5001.5   51.49  5002.2   53.81  5002.9   54.35
  5042.9   58.36  5061.9   66.57  5072.5   66.98  5086.4    65.9  5136.4    66.8
  5505.9    66.3  5675.9      67  5745.9    65.9  5785.9    66.3  5835.9      68
  5875.9    67.6  5905.9    68.4  6265.9    69.3  6285.9    70.3  6686.5    70.5
#Mann= 5 , 1 , 0
  3625.9      .2       0  3625.9     .14       0  4946.9     .04       0
  5061.9     .14       0  6686.5      .2       0
Bank Sta=4946.9,5061.9
XS Rating Curve= 0
Exp/Cntr=.3,.1

Type RM Length L Ch R = 1 ,16706.8 ,588.4,591.7,600.5
BEGIN DESCRIPTION:
Cross Section 16706.8-Interpolated
END DESCRIPTION:
XS GIS Cut Line= 6
      3171224.53     13919636.48       3170601.8     13919644.47
      3169873.78     13919641.86      3169611.73     13919660.67
      3169078.43      13919665.8       3167887.3      13919676.4
#Sta/Elev= 30
  3518.7    66.2  3648.7    65.1  4321.5    65.5  4631.5    64.6  4929.5    65.7
    4939   66.48  4957.1   58.31  4993.9   53.67  4995.6   51.98  4999.6   50.76
  5003.3   51.87  5006.1   53.68  5044.4   56.98  5065.5   65.88  5099.5    65.7
  5132.2    66.6  5422.2    66.5  5462.2    65.9  5492.2    64.4  5632.2    64.5
  5675.6    66.6  5865.6    67.6  5935.6    67.1  5945.6    66.2  5965.6      66
  5985.6    66.2  6005.6    67.7  6035.6    68.4  6812.5   69.28  6856.7    69.4
#Mann= 6 , 1 , 0
  3518.7      .2       0  3518.7     .14       0    4939     .04       0
  5065.5     .14       0  6812.5      .1       0  6856.7      .2       0
Bank Sta=4939,5065.5
XS Rating Curve= 0
Exp/Cntr=.3,.1

Type RM Length L Ch R = 1 ,16115.1 ,957.4,958.8,962
BEGIN DESCRIPTION:
Cross Section 16115.1
END DESCRIPTION:
XS GIS Cut Line= 5
      3171623.73     13919069.63      3170255.25     13919059.85
      3169408.29     13919059.85      3168466.46     13919005.64
      3168023.02     13918997.78
#Sta/Elev= 30
  3140.5    66.8  3360.6   66.54  3620.5    66.1  3730.5    67.9  3880.5    65.3
  4010.5    66.6    4629      65  4938.9   66.58  4957.1   58.41  4993.9   53.77
  4999.6   50.86  5006.1   53.78  5044.4   57.08  5065.5   65.98    5229    63.6
    5259      64    5289    66.6    5406    67.4    5476    66.4    5506      64
    5556    63.9    5586    66.7    5846      69    6026      69    6256    66.6
  6339.4    68.1  6529.4    68.3  6559.4      67  6679.2    68.9  6742.9    68.3
#Mann= 6 , 1 , 0
  3140.5      .2       0  3360.6     .14       0  4938.9     .04       0
  5065.5     .14       0  6679.2      .1       0  6742.9      .2       0
Bank Sta=4938.9,5065.5
XS Rating Curve= 0
Exp/Cntr=.3,.1

Type RM Length L Ch R = 1 ,15156.3 ,413,415.9,419.8
BEGIN DESCRIPTION:
Cross Section 15156.3
END DESCRIPTION:
XS GIS Cut Line= 6
      3171671.37     13918192.56      3170289.13     13918165.45
      3169930.01     13918104.47      3169577.68      13918097.7
      3169218.57      13918097.7      3168458.76      13918114.7
#Sta/Elev= 30
    3126    70.8    3226    70.7    3311    69.7    3466      69    3506    67.8
    3611    67.1  3901.3   65.84    3971    65.5    4101    67.1    4426    66.9
  4508.5    67.4  4748.5    66.5  4798.5    65.2  4813.5    65.7  4872.8    65.3
    4908   63.71  4939.1   65.75  4949.6   58.95  4995.2   53.65  4999.1   50.34
    5003   50.98  5004.9   53.75  5034.4   57.39  5065.6   65.22  5095.8   64.69
  5117.8    65.7  5360.2      66  5530.2    67.9  5794.3    66.1  6344.3    66.5
#Mann= 4 , 1 , 0
    3126      .2       0  3901.3     .14       0  4939.1     .04       0
  5065.6      .1       0
Bank Sta=4939.1,5065.6
XS Rating Curve= 0
Exp/Cntr=.3,.1