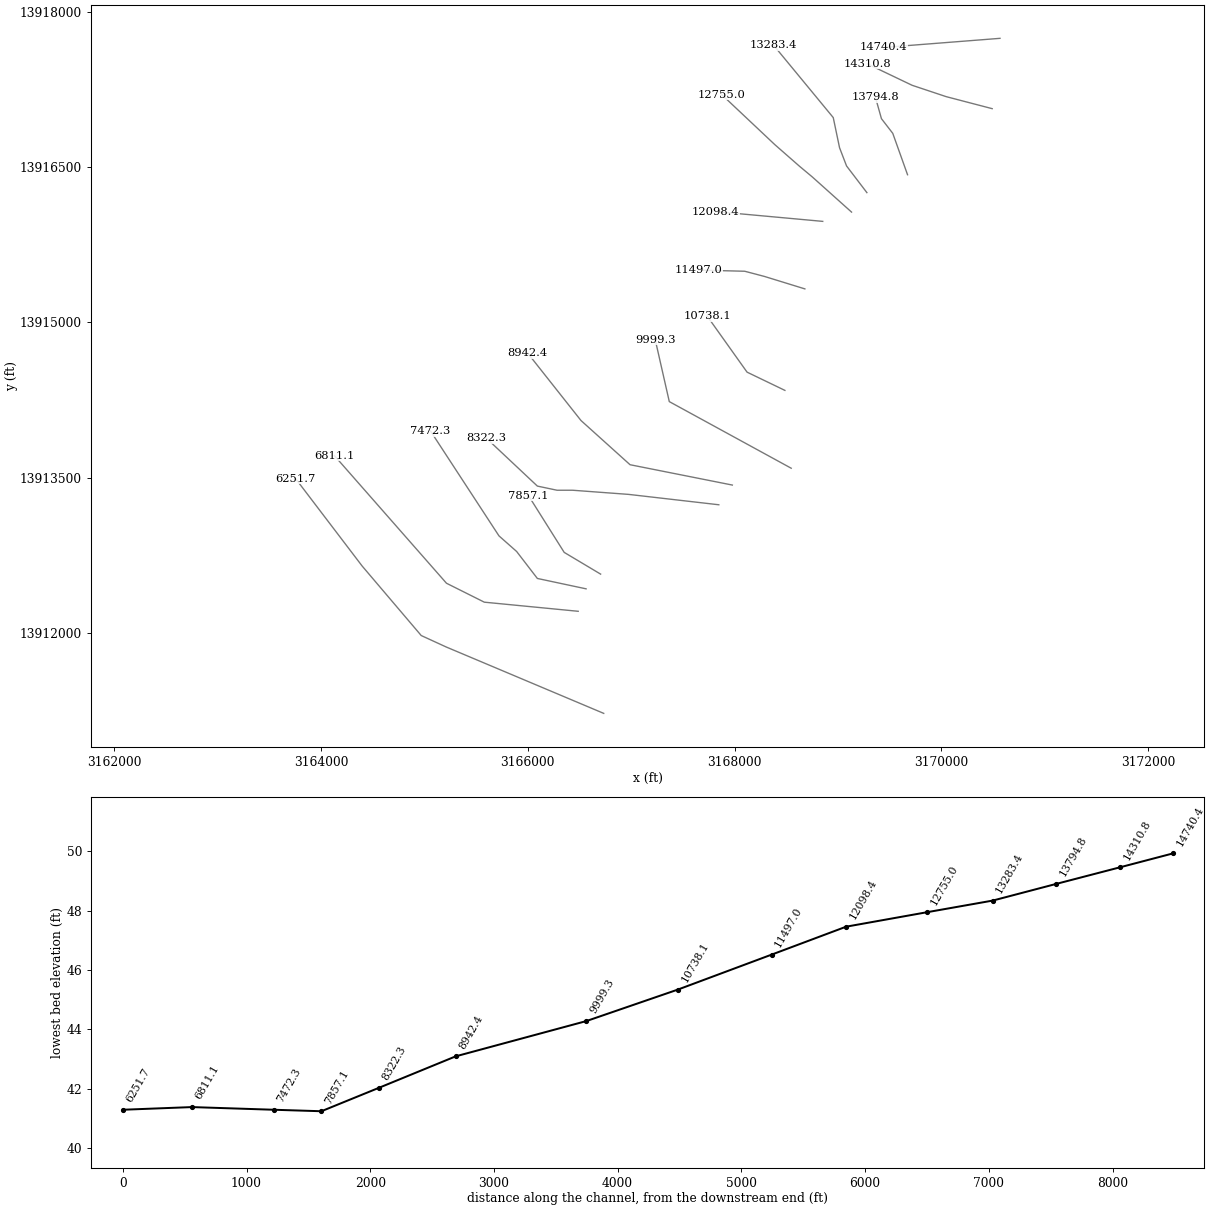
HEC-RAS study P130-02-00.PRJ: P130-02-00

--- P130-02-00.g01 (geometry) --- (continued)

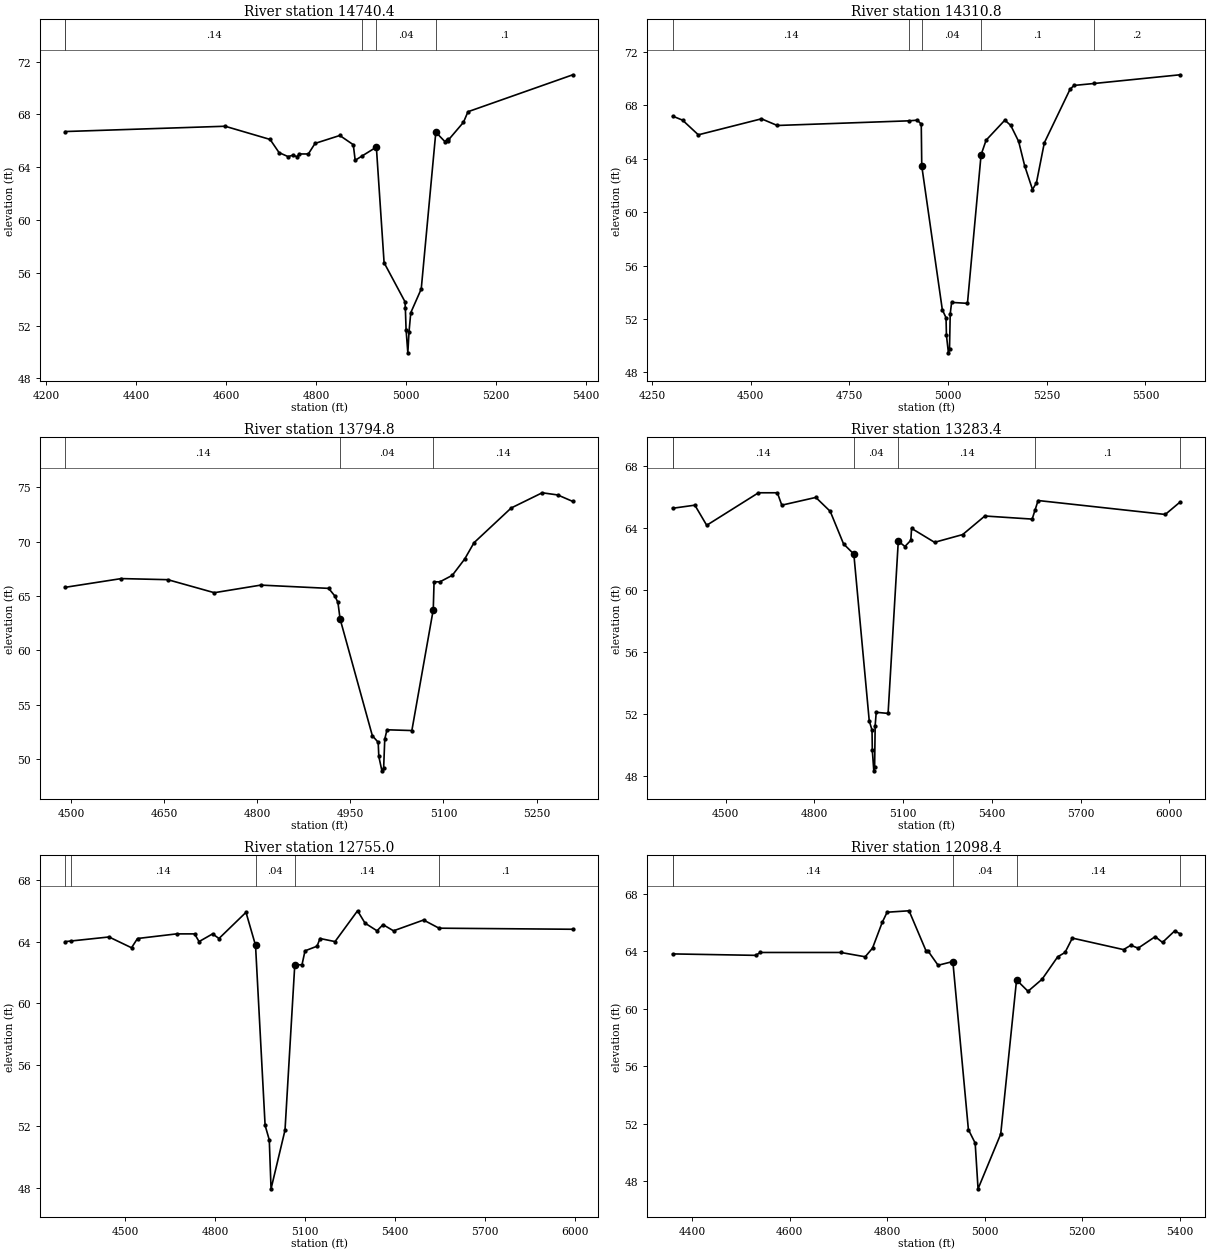
Type RM Length L Ch R = 1 ,14740.4 ,450.5,429.6,398.6
BEGIN DESCRIPTION:
Cross Section 14740.4
END DESCRIPTION:
XS GIS Cut Line= 2
      3170566.93     13917745.36      3169442.16     13917657.28
#Sta/Elev= 30
  4242.6    66.7  4597.6    67.1  4697.6    66.1  4717.6    65.1  4737.6    64.8
  4747.6    64.9  4757.6    64.8  4762.6      65  4782.6      65  4797.6    65.8
  4852.6    66.4  4882.6    65.7  4886.8   64.52  4901.8   64.84  4933.9   65.52
  4951.1   56.76  4997.6    53.8  4998.4   53.29    5000   51.67  5003.9   49.93
  5006.5   51.51  5010.4   52.97  5033.7   54.77  5066.1   66.65  5086.2   65.94
  5092.5   66.15  5092.6      66  5127.6    67.4  5137.6    68.2  5370.8      71
#Mann= 5 , 1 , 0
  4242.6      .2       0  4242.6     .14       0  4901.8      .1       0
  4933.9     .04       0  5066.1      .1       0
Bank Sta=4933.9,5066.1
XS Rating Curve= 0
Exp/Cntr=.3,.1

Type RM Length L Ch R = 1 ,14310.8 ,547.1,516,462.1
BEGIN DESCRIPTION:
Cross Section 14310.8-Interpolated
END DESCRIPTION:
XS GIS Cut Line= 5
      3170491.27     13917065.92      3170046.12     13917182.04
      3169833.23     13917253.01      3169717.11     13917291.72
      3169284.87     13917498.16
#Sta/Elev= 30
  4301.9    67.2  4326.9    66.9  4366.9    65.8  4526.9      67  4566.9    66.5
  4901.8   66.85  4921.9    66.9  4931.9    66.6  4933.2   63.46  4985.3   52.69
  4994.7   52.09  4995.7   50.79  5000.7   49.46  5003.5   49.72  5005.3   52.38
  5008.9   53.24    5049   53.17  5083.5    64.3  5096.3    65.4  5143.8    66.9
  5158.8    66.5  5178.8    65.3  5193.8    63.5  5213.8    61.7  5223.8    62.2
  5243.8    65.2  5308.8    69.2  5318.8    69.5  5370.8   69.65  5587.8    70.3
#Mann= 5 , 1 , 0
  4301.9     .14       0  4901.8      .1       0  4933.2     .04       0
  5083.5      .1       0  5370.8      .2       0
Bank Sta=4933.2,5083.5
XS Rating Curve= 0
Exp/Cntr=.3,.1

Type RM Length L Ch R = 1 ,13794.8 ,533,511.4,463.6
BEGIN DESCRIPTION:
Cross Section 13794.8-Interpolated
END DESCRIPTION:
XS GIS Cut Line= 4
      3169672.78     13916427.56      3169530.02     13916827.22
      3169420.35     13916969.15      3169362.28     13917175.59
#Sta/Elev= 27
  4490.4    65.8  4580.4    66.6  4655.4    66.5  4730.4    65.3  4805.4      66
  4914.8    65.7  4924.8      65  4929.8    64.4  4933.2    62.9  4985.3   52.13
  4994.7   51.53  4995.7   50.23  5000.7    48.9  5003.5   49.16  5005.3   51.82
  5008.9   52.68    5049   52.61  5083.5   63.74  5084.8    66.3  5094.2    66.3
  5114.2    66.9  5134.2    68.4  5149.2    69.9  5209.2    73.1  5259.2    74.5
  5284.2    74.3  5308.6    73.7
#Mann= 3 , 1 , 0
  4490.4     .14       0  4933.2     .04       0  5083.5     .14       0
Bank Sta=4933.2,5083.5
XS Rating Curve= 0
Exp/Cntr=.3,.1

Type RM Length L Ch R = 1 ,13283.4 ,457.1,528.4,553.9
BEGIN DESCRIPTION:
Cross Section 13283.4
END DESCRIPTION:
XS GIS Cut Line= 5
      3169279.55     13916254.71      3169083.05     13916512.19
       3169015.3     13916688.35      3168954.31     13916979.71
      3168378.38      13917677.6
#Sta/Elev= 30
  4320.8    65.3  4395.8    65.5  4435.8    64.2  4610.8    66.3  4674.7    66.3
  4689.7    65.5  4804.7      66  4853.4    65.1  4898.4      63  4933.2   62.34
  4985.3   51.57  4994.7   50.97  4995.7   49.67  5000.7   48.34  5003.5    48.6
  5005.3   51.26  5008.9   52.12    5049   52.05  5083.5   63.18  5105.9   62.83
  5125.8   63.23  5128.4      64  5206.1    63.1  5301.1    63.6  5376.1    64.8
  5536.1    64.6  5545.9   65.19  5556.1    65.8  5986.1    64.9    6036    65.7
#Mann= 6 , 1 , 0
  4320.8      .2       0  4320.8     .14       0  4933.2     .04       0
  5083.5     .14       0  5545.9      .1       0    6036      .2       0
Bank Sta=4933.2,5083.5
XS Rating Curve= 0
Exp/Cntr=.3,.1

Type RM Length L Ch R = 1 ,12755.0 ,609.4,656.6,705
BEGIN DESCRIPTION:
Cross Section 12755.0-Interpolated
END DESCRIPTION:
XS GIS Cut Line= 5
       3169131.3     13916066.57      3168750.26     13916407.51
      3168629.93     13916507.78      3168389.27     13916718.36
      3167877.88     13917199.67
#Sta/Elev= 30
  4301.6      64  4320.8   64.04  4446.6    64.3  4521.6    63.6  4541.6    64.2
  4671.6    64.5  4731.6    64.5  4746.6      64  4791.6    64.5  4812.9    64.2
  4902.9    65.9 4934.65   63.76 4966.55   52.07 4980.45   51.13 4986.35   47.95
 5032.85   51.76 5065.35   62.48  5089.5    62.5  5099.5    63.4  5139.5    63.7
  5149.5    64.2  5199.5      64  5274.5      66  5299.3    65.2  5339.3    64.7
  5359.3    65.1  5394.3    64.7  5494.3    65.4  5545.9   64.87  5991.6    64.8
#Mann= 5 , 1 , 0
  4301.6      .2       0  4320.8     .14       0 4934.65     .04       0
 5065.35     .14       0  5545.9      .1       0
Bank Sta=4934.65,5065.35
XS Rating Curve= 0
Exp/Cntr=.3,.1

Type RM Length L Ch R = 1 ,12098.4 ,622.2,601.4,580.5
BEGIN DESCRIPTION:
Cross Section 12098.4
END DESCRIPTION:
XS GIS Cut Line= 2
      3168852.68     13915976.91        3167816.     13916071.77
#Sta/Elev= 30
  4359.8    63.8  4529.8    63.7  4539.8    63.9  4704.8    63.9  4754.8    63.6
  4769.8    64.2  4789.8      66  4799.8    66.7  4844.8    66.8  4879.8      64
 4883.15   64.03 4904.35   63.01 4934.65   63.27 4966.55   51.58 4980.45   50.64
 4986.35   47.46 5032.85   51.27 5065.35   61.99 5088.85    61.2 5117.75   62.04
  5149.8    63.6  5164.8    63.9  5179.8    64.9  5284.8    64.1  5299.8    64.4
  5314.8    64.2  5349.8      65  5364.8    64.6  5389.8    65.4  5400.8    65.2
#Mann= 5 , 1 , 0
  4359.8      .2       0  4359.8     .14       0 4934.65     .04       0
 5065.35     .14       0  5400.8      .2       0
Bank Sta=4934.65,5065.35
XS Rating Curve= 0
Exp/Cntr=.3,.1

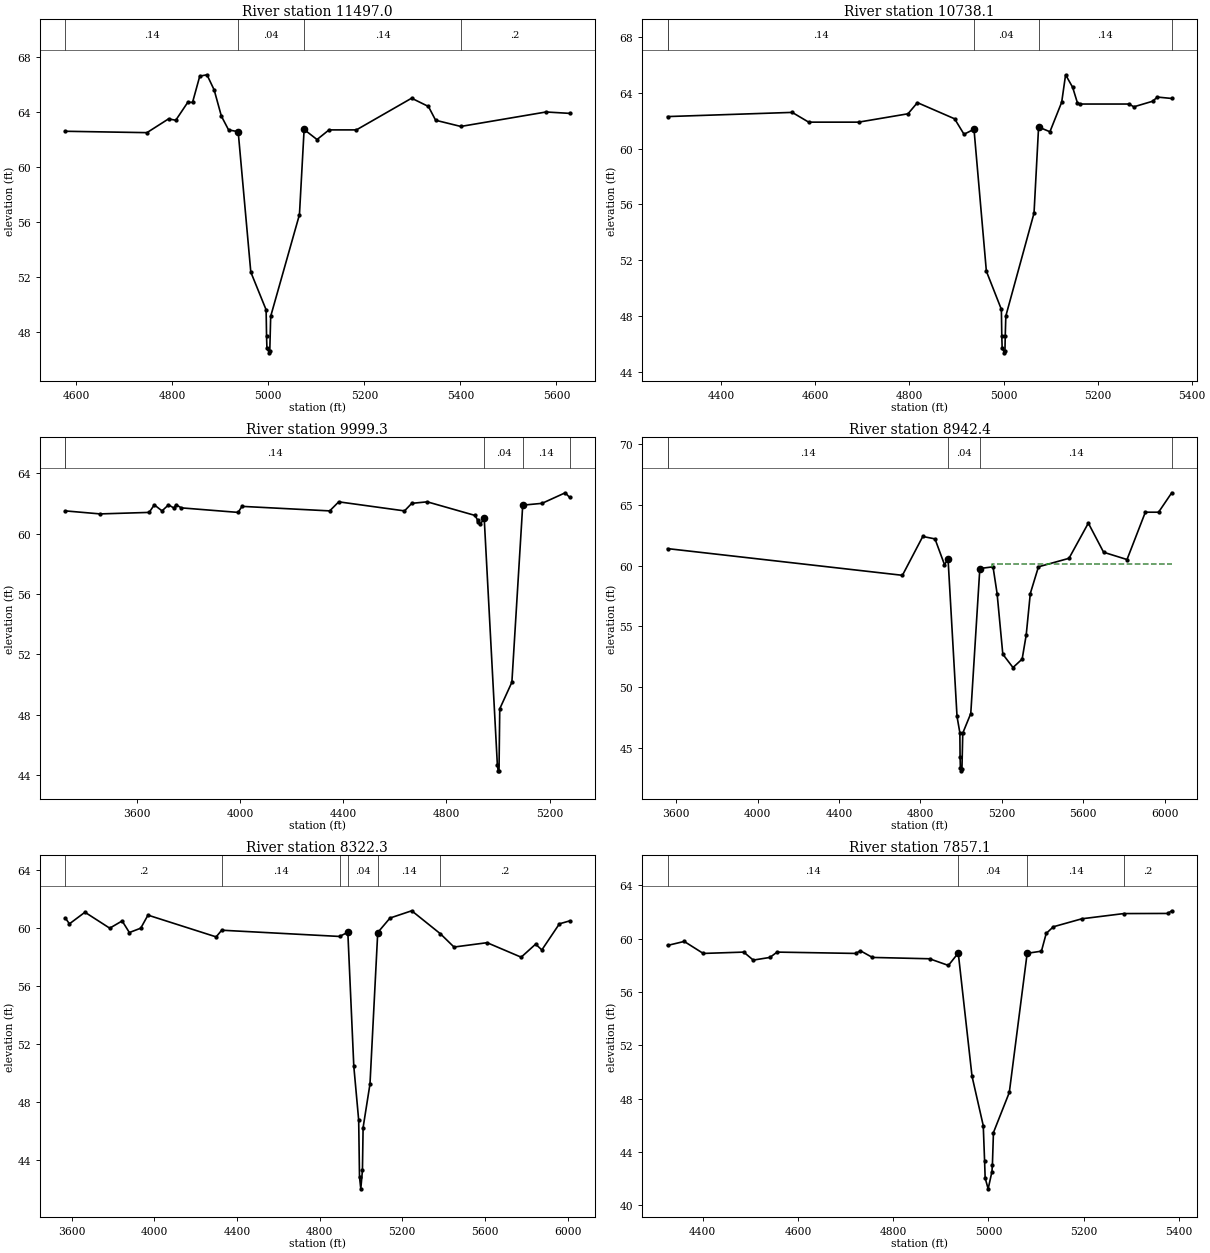
Type RM Length L Ch R = 1 ,11497.0 ,813.7,758.9,700.4
BEGIN DESCRIPTION:
Cross Section 11497.0-Interpolated
END DESCRIPTION:
XS GIS Cut Line= 4
      3168680.07     13915324.55        3168289.     13915444.88
      3168098.48     13915495.01      3167654.81     13915506.18
#Sta/Elev= 30
  4577.2    62.6  4747.2    62.5  4792.2    63.5  4807.2    63.4  4832.2    64.7
  4842.2    64.7  4857.2    66.6  4872.2    66.7  4887.2    65.6  4902.2    63.7
  4917.2    62.7  4937.2   62.57  4963.5   52.38  4995.4   49.64  4996.3   47.71
  4997.1   46.85    5002   46.52    5003   46.65  5004.9   49.17  5064.8   56.55
  5074.5   62.73  5101.4      62  5126.4    62.7  5183.4    62.7  5298.4      65
  5333.4    64.4  5348.4    63.4  5400.8   62.95  5578.4      64  5627.2    63.9
#Mann= 4 , 1 , 0
  4577.2     .14       0  4937.2     .04       0  5074.5     .14       0
  5400.8      .2       0
Bank Sta=4937.2,5074.5
XS Rating Curve= 0
Exp/Cntr=.3,.1

Type RM Length L Ch R = 1 ,10738.1 ,751.8,738.8,679.4
BEGIN DESCRIPTION:
Cross Section 10738.1
END DESCRIPTION:
XS GIS Cut Line= 3
      3168486.79     13914343.96       3168120.9     13914520.13
      3167734.69     13915062.19
#Sta/Elev= 30
  4285.8    62.3  4550.8    62.6  4585.8    61.9  4691.9    61.9  4796.9    62.5
  4816.9    63.3    4896   62.14    4916   61.03  4937.2   61.39  4963.5    51.2
  4995.4   48.46  4996.3   46.53  4997.1   45.67    5002   45.34    5003   45.47
  5003.6   46.56  5004.9   47.99  5064.8   55.37  5074.5   61.55  5098.6   61.21
  5123.6   63.33  5131.9    65.3  5146.9    64.4  5156.9    63.3  5161.9    63.2
  5266.9    63.2  5276.9      63  5316.9    63.4  5326.9    63.7  5357.5    63.6
#Mann= 5 , 1 , 0
  4285.8      .2       0  4285.8     .14       0  4937.2     .04       0
  5074.5     .14       0  5357.5      .2       0
Bank Sta=4937.2,5074.5
XS Rating Curve= 0
Exp/Cntr=.3,.1

Type RM Length L Ch R = 1 ,9999.3  ,941.7,1056.9,1059.6
BEGIN DESCRIPTION:
Cross Section 9999.3
END DESCRIPTION:
XS GIS Cut Line= 3
      3168547.77     13913591.86       3167368.8     13914235.55
      3167233.29     13914831.81
#Sta/Elev= 30
  3322.4    61.5  3457.4    61.3  3647.4    61.4  3667.4    61.9  3697.4    61.5
  3722.4    61.9  3742.4    61.7  3752.4    61.9  3772.4    61.7  3992.4    61.4
  4007.4    61.8  4347.4    61.5  4382.4    62.1  4637.4    61.5  4665.6      62
  4725.6    62.1  4910.6    61.2  4920.6    60.9  4921.1   60.78  4931.7   60.62
  4946.4   61.02  4997.4   44.68  5000.5   44.29  5003.8   44.28  5006.7   48.39
  5053.7   50.15  5095.7   61.88  5170.6      62  5260.6    62.7  5277.1    62.4
#Mann= 5 , 1 , 0
  3322.4      .2       0  3322.4     .14       0  4946.4     .04       0
  5095.7     .14       0  5277.1      .2       0
Bank Sta=4946.4,5095.7
XS Rating Curve= 0
Exp/Cntr=.3,.1

Type RM Length L Ch R = 1 ,8942.4  ,565.3,620.1,697.8
BEGIN DESCRIPTION:
Cross Section 8942.4
END DESCRIPTION:
XS GIS Cut Line= 4
      3167978.62     13913429.25      3166989.36     13913625.74
      3166515.07     13914052.61      3166000.11     13914703.08
#Sta/Elev= 30
    3558    61.4  4711.6    59.2  4811.6    62.4  4871.6    62.2  4918.2   60.08
  4935.8   60.52  4979.8   47.57  4993.7   46.23  4994.8   44.26  4996.3   43.35
  5000.4   43.09    5004   43.26    5008    46.2  5047.3   47.81  5091.8   59.76
  5156.6    59.9  5176.6    57.7  5204.7    52.7  5254.7    51.6  5299.7    52.3
  5319.7    54.3  5339.7    57.7  5379.7    59.9  5529.7    60.6  5624.7    63.5
  5699.7    61.1  5814.7    60.5  5904.7    64.4  5969.7    64.4  6034.3      66
#Mann= 5 , 1 , 0
    3558      .2       0    3558     .14       0  4935.8     .04       0
  5091.8     .14       0  6034.3      .2       0
#XS Ineff= 2 , 0
       0                  5151.6       0    60.1
Permanent Ineff=
       F       F
Bank Sta=4935.8,5091.8
XS Rating Curve= 0
Exp/Cntr=.3,.1

Type RM Length L Ch R = 1 ,8322.3  ,513.8,465.2,385.6
BEGIN DESCRIPTION:
Cross Section 8322.3-Interpolated
END DESCRIPTION:
XS GIS Cut Line= 6
      3167847.79     13913238.85      3166975.41     13913339.12
      3166433.93     13913379.23      3166283.52     13913379.23
        3166093.     13913419.34      3165601.66      13913880.6
#Sta/Elev= 30
  3569.2    60.7  3589.2    60.3  3664.2    61.1  3784.2      60  3844.2    60.5
  3879.2    59.7  3934.2      60  3969.2    60.9  4299.2    59.4    4326   59.86
  4896.6   59.43  4936.5   59.72  4965.4   50.48    4989   46.77    4993   42.84
  4999.3   42.03  5007.2   43.31  5010.4   46.25  5043.7   49.26  5081.2    59.7
  5140.7    60.7  5245.7    61.2  5384.8   59.61  5450.4    58.7  5610.4      59
  5775.4      58  5845.4    58.9  5875.4    58.5  5960.4    60.3  6009.3    60.5
#Mann= 6 , 1 , 0
  3569.2      .2       0    4326     .14       0  4896.6     .14       0
  4936.5     .04       0  5081.2     .14       0  5384.8      .2       0
Bank Sta=4936.5,5081.2
XS Rating Curve= 0
Exp/Cntr=.3,.1

Type RM Length L Ch R = 1 ,7857.1  ,379.9,384.8,405.4
BEGIN DESCRIPTION:
Cross Section 7857.1
END DESCRIPTION:
XS GIS Cut Line= 3
      3166704.79     13912568.73      3166352.45     13912778.78
      3166006.89     13913327.61
#Sta/Elev= 30
    4326    59.5    4361    59.8    4401    58.9    4486      59    4506    58.4
    4541    58.6    4556      59    4721    58.9    4731    59.1  4756.2    58.6
  4876.2    58.5  4915.8      58  4936.5   58.93  4965.4   49.69    4989   45.98
  4991.8   43.34    4993   42.05  4999.3   41.24  5007.2   42.52  5008.2   43.01
  5010.4   45.46  5043.7   48.47  5081.2   58.91  5111.2   59.07  5121.2    60.4
  5136.2    60.9  5196.2    61.5    5284   61.89  5376.2    61.9  5384.8    62.1
#Mann= 4 , 1 , 0
    4326     .14       0  4936.5     .04       0  5081.2     .14       0
    5284      .2       0
Bank Sta=4936.5,5081.2
XS Rating Curve= 0
Exp/Cntr=.3,.1

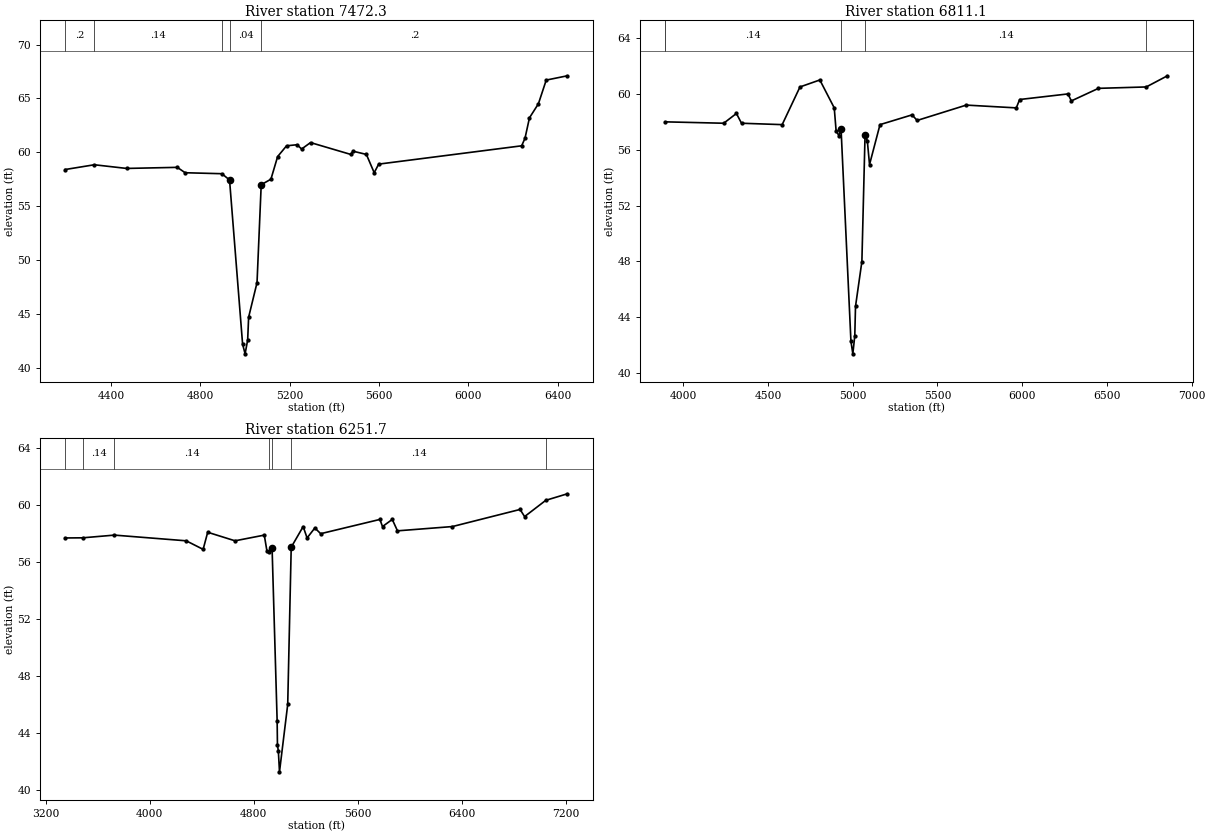
Type RM Length L Ch R = 1 ,7472.3  ,625.6,661.2,688.4
BEGIN DESCRIPTION:
Cross Section 7472.3-Interpolated
END DESCRIPTION:
XS GIS Cut Line= 5
      3166564.29     13912426.63        3166093.      13912526.9
      3165892.45     13912787.61      3165721.98     13912938.02
      3165060.18     13913950.79
#Sta/Elev= 30
  4195.5    58.4    4326   58.84  4470.5    58.5  4697.3    58.6  4732.3    58.1
  4896.6   58.01  4931.1   57.43  4989.5   42.19  5000.7   41.29  5012.2   42.58
  5016.5   44.69  5054.1    47.9  5072.8   56.99  5116.3    57.5  5146.3    59.6
  5186.3    60.6  5233.6    60.7  5253.6    60.3  5293.6    60.9  5473.6    59.8
  5483.6    60.1  5543.6    59.8  5578.6    58.1  5598.6    58.9  6238.6    60.6
  6253.6    61.3  6273.6    63.2  6313.6    64.5  6348.6    66.7  6443.4    67.1
#Mann= 5 , 1 , 0
  4195.5      .2       0    4326     .14       0  4896.6     .14       0
  4931.1     .04       0  5072.8      .2       0
Bank Sta=4931.1,5072.8
XS Rating Curve= 0
Exp/Cntr=.3,.1

Type RM Length L Ch R = 1 ,6811.1  ,561.6,559.4,557.8
BEGIN DESCRIPTION:
Cross Section 6811.1
END DESCRIPTION:
XS GIS Cut Line= 4
      3166487.96     13912209.62      3165580.02      13912297.7
      3165214.13     13912480.65      3164130.02     13913713.82
#Sta/Elev= 30
  3893.8      58  4238.8    57.9  4313.8    58.6  4343.8    57.9  4583.8    57.8
  4688.8    60.5    4806      61    4891      59    4902   57.36  4918.9      57
  4931.1   57.52  4989.5   42.28  5000.7   41.38  5012.2   42.67  5016.5   44.78
  5054.1   47.99  5072.8   57.08  5086.2   56.64  5099.2   54.94    5161    57.8
  5350.1    58.5  5380.1    58.1  5670.1    59.2  5965.1      59  5985.1    59.6
  6270.1      60  6290.1    59.5  6450.1    60.4  6732.1    60.5    6857    61.3
#Mann= 5 , 1 , 0
  3893.8      .2       0  3893.8     .14       0  4931.1     .04       0
  5072.8     .14       0  6732.1      .2       0
Bank Sta=4931.1,5072.8
XS Rating Curve= 0
Exp/Cntr=.3,.1

Type RM Length L Ch R = 1 ,6251.7  ,552.2,518.6,472.3
BEGIN DESCRIPTION:
Cross Section 6251.7-Interpolated
END DESCRIPTION:
XS GIS Cut Line= 5
      3166734.75     13911223.34      3165210.59     13911865.09
      3164969.93     13911975.39      3164398.37     13912647.23
      3163756.61     13913489.53
#Sta/Elev= 30
  3350.9    57.7  3485.1   57.71  3729.1    57.9  4280.9    57.5  4410.9    56.9
  4445.9    58.1  4655.9    57.5  4880.9    57.9  4900.9    56.8  4917.6   56.72
  4940.7   57.01  4979.7   44.85    4982   43.15  4988.8   42.77  4997.7   41.29
  5060.9   46.02  5087.8   57.05  5179.7    58.5  5209.7    57.7  5269.4    58.4
  5314.4      58  5769.4      59  5789.4    58.5  5864.4      59  5904.4    58.2
  6326.5    58.5  6846.5    59.7  6881.5    59.2  7044.2   60.34  7210.4    60.8
#Mann= 7 , 1 , 0
  3350.9      .2       0  3485.1     .14       0  3729.1     .14       0
  4917.6     .14       0  4940.7     .04       0  5087.8     .14       0
  7044.2      .2       0
Bank Sta=4940.7,5087.8
XS Rating Curve= 0
Exp/Cntr=.3,.1