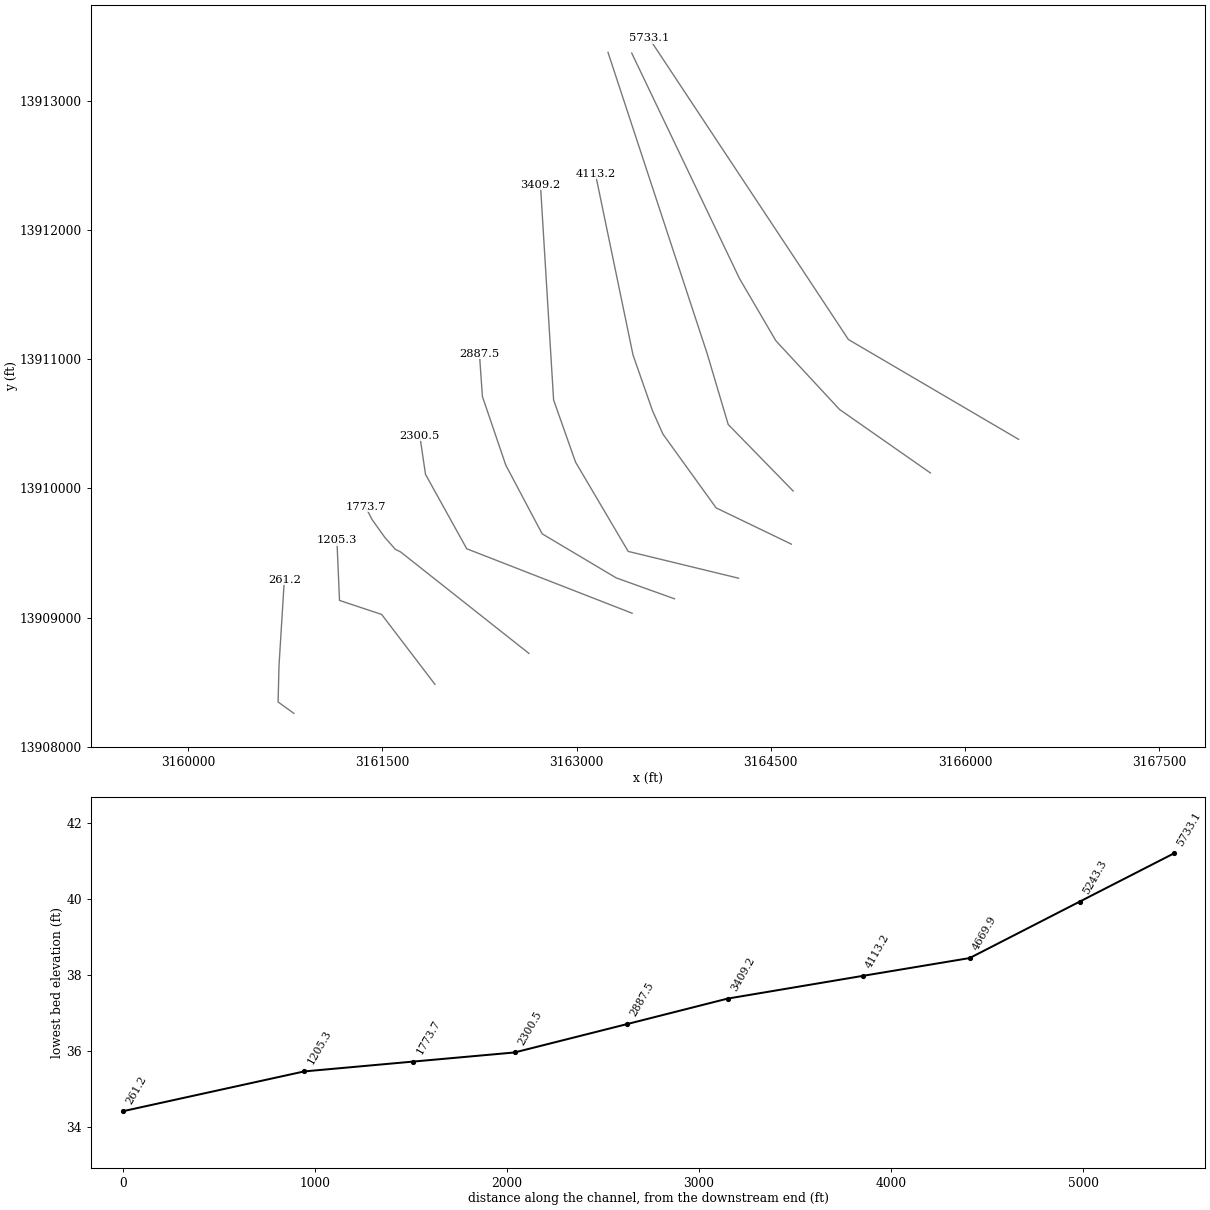
HEC-RAS study P130-02-00.PRJ: P130-02-00

--- P130-02-00.g01 (geometry) --- (continued)

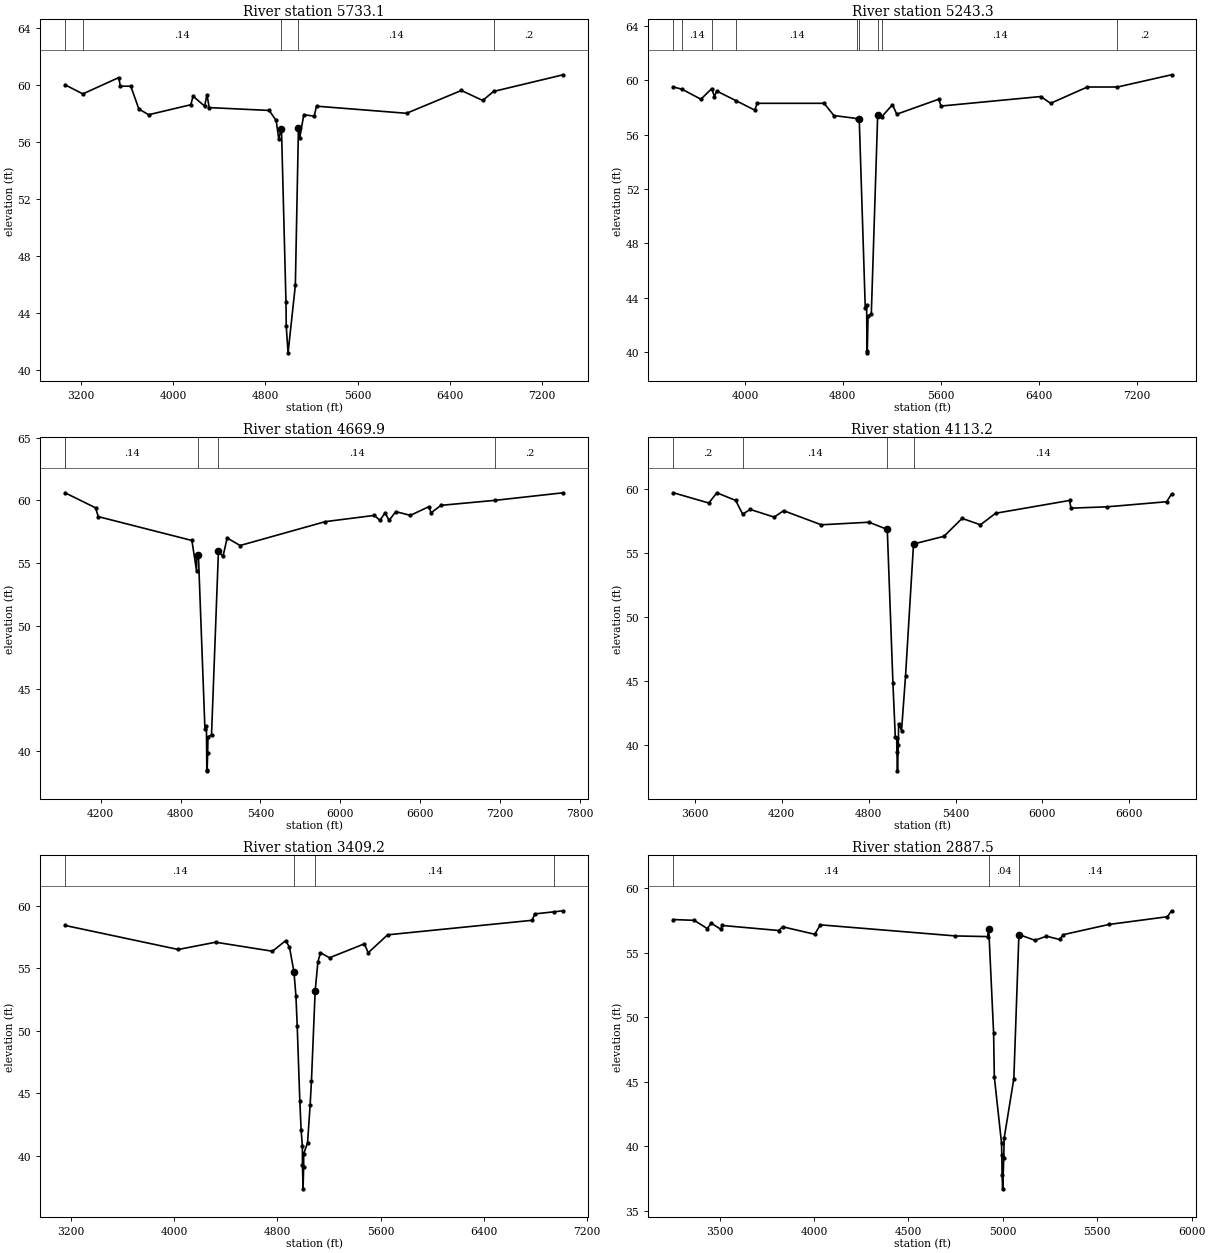
Type RM Length L Ch R = 1 ,5733.1  ,478.6,489.8,499.7
BEGIN DESCRIPTION:
Cross Section 5733.1
END DESCRIPTION:
XS GIS Cut Line= 4
      3166413.43     13910380.18      3165098.95     13911152.61
      3164733.06     13911708.22      3163560.86     13913483.45
#Sta/Elev= 30
  3064.7      60  3219.1   59.36  3529.7    60.5  3544.7    59.9  3634.7    59.9
  3704.7    58.3  3789.7    57.9  4154.7    58.6  4174.7    59.2  4274.7    58.5
  4294.7    59.3  4314.7    58.4  4834.3    58.2  4894.3    57.5  4917.1   56.22
  4940.7   56.93  4979.7   44.77    4982   43.07  4997.7   41.21  5060.9   45.94
  5087.8   56.97  5099.3    56.3  5134.3    57.9  5224.3    57.8  5244.3    58.5
  6024.6      58  6499.6    59.6  6684.6    58.9  6778.2   59.53  7381.9    60.7
#Mann= 5 , 1 , 0
  3064.7      .2       0  3219.1     .14       0  4940.7     .04       0
  5087.8     .14       0  6778.2      .2       0
Bank Sta=4940.7,5087.8
XS Rating Curve= 0
Exp/Cntr=.3,.1

Type RM Length L Ch R = 1 ,5243.3  ,597.8,573.4,552.4
BEGIN DESCRIPTION:
Cross Section 5243.3-Interpolated
END DESCRIPTION:
XS GIS Cut Line= 5
      3165732.01     13910120.32      3165030.09     13910611.66
      3164538.75     13911143.12      3164257.98     13911624.43
      3163425.71      13913369.2
#Sta/Elev= 30
  3414.9    59.5  3485.1   59.34  3639.9    58.6  3729.1   59.39  3749.9    58.8
  3769.9    59.2  3927.8   58.49  4079.9    57.8  4099.9    58.3  4646.7    58.3
  4726.7    57.4  4917.6   57.18    4934   57.13  4983.1   43.27  4994.3   43.48
  4997.3   40.04  4999.3   39.94  5005.9   42.63  5032.6   42.81  5084.6   57.43
  5116.4   57.29  5205.5    58.2  5240.5    57.5  5582.7    58.6  5602.7    58.1
  6417.7    58.8  6497.7    58.3  6797.7    59.5  7044.2    59.5  7485.8    60.4
#Mann= 9 , 1 , 0
  3414.9      .2       0  3485.1     .14       0  3729.1    .035       0
  3927.8     .14       0  4917.6    .035       0    4934     .04       0
  5084.6    .035       0  5116.4     .14       0  7044.2      .2       0
Bank Sta=4934,5084.6
XS Rating Curve= 0
Exp/Cntr=.3,.1

Type RM Length L Ch R = 1 ,4669.9  ,534.7,556.7,559.8
BEGIN DESCRIPTION:
Cross Section 4669.9
END DESCRIPTION:
XS GIS Cut Line= 4
      3164672.08     13909980.42      3164170.68     13910495.37
      3164008.06      13911044.2      3163242.41     13913375.04
#Sta/Elev= 30
  3931.3    60.6  4161.3    59.4  4181.3    58.7    4885    56.8    4920    54.4
  4921.2   55.51    4934   55.64  4983.1   41.78  4994.3   41.99  4997.3   38.55
  4999.3   38.45  5003.8   39.88  5005.9   41.14  5032.6   41.32  5084.6   55.94
    5119   55.53    5150      57  5247.5    56.4  5887.5    58.3  6257.5    58.8
  6297.5    58.4  6337.5      59  6367.5    58.4  6417.5    59.1  6527.5    58.8
  6667.5    59.5  6682.5      59  6757.5    59.6  7166.4      60  7675.8    60.6
#Mann= 5 , 1 , 0
  3931.3      .2       0  3931.3     .14       0    4934     .04       0
  5084.6     .14       0  7166.4      .2       0
Bank Sta=4934,5084.6
XS Rating Curve= 0
Exp/Cntr=.3,.1

Type RM Length L Ch R = 1 ,4113.2  ,703.5,704,704.8
BEGIN DESCRIPTION:
Cross Section 4113.2-Interpolated
END DESCRIPTION:
XS GIS Cut Line= 6
      3164659.08     13909568.81      3164077.49     13909849.58
      3163666.37     13910421.14      3163586.15     13910601.64
      3163435.74     13911032.82      3163144.94     13912436.65
#Sta/Elev= 30
  3452.8    59.7  3697.8    58.9  3752.8    59.7  3882.8    59.1  3931.3   58.03
  3982.8    58.4  4148.6    57.8  4213.6    58.3  4473.6    57.2  4802.7    57.4
    4929   56.84    4968   44.84  4984.3   40.64  4994.1   40.53  4995.3   39.48
  4999.5   37.98  5005.2   40.02  5007.4   41.67  5027.5   41.13  5054.9   45.37
  5110.2    55.7  5320.2    56.3  5445.2    57.7  5571.9    57.2  5676.9    58.1
  6186.9    59.1  6196.9    58.5  6441.9    58.6  6856.9      59  6890.5    59.6
#Mann= 4 , 1 , 0
  3452.8      .2       0  3931.3     .14       0    4929     .04       0
  5110.2     .14       0
Bank Sta=4929,5110.2
XS Rating Curve= 0
Exp/Cntr=.3,.1

Type RM Length L Ch R = 1 ,3409.2  ,506.7,521.7,523.4
BEGIN DESCRIPTION:
Cross Section 3409.2
END DESCRIPTION:
XS GIS Cut Line= 5
      3164250.26     13909305.55      3163398.25      13909512.9
      3162991.71     13910204.02      3162822.31     13910685.09
      3162720.68     13912351.91
#Sta/Elev= 30
  3155.6   58.41  4032.5   56.49  4322.5   57.07  4762.5   56.35  4864.3   57.19
  4894.3   56.68    4929   54.69  4944.3   52.78  4954.3   50.36  4974.3   44.42
  4984.3   42.11  4994.3   40.78  4994.7   39.27  4999.5   37.38  5004.2   39.13
  5004.3   40.17  5034.3   41.06  5054.3   44.07  5064.3   45.95  5093.1   53.16
  5114.3   55.49  5134.3   56.23  5204.3   55.83  5474.3   56.94  5504.3   56.23
  5654.3   57.66  6774.3   58.82  6794.3   59.33  6945.4    59.5  7014.2   59.58
#Mann= 4 , 1 , 0
  3155.6     .14       0    4929     .04       0  5093.1     .14       0
  6945.4      .2       0
Bank Sta=4929,5093.1
XS Rating Curve= 0
Exp/Cntr=.3,.1

Type RM Length L Ch R = 1 ,2887.5  ,576.7,587,611.7
BEGIN DESCRIPTION:
Cross Section 2887.5-Interpolated
END DESCRIPTION:
XS GIS Cut Line= 6
      3163755.57      13909146.2      3163305.38      13909308.1
      3162733.82     13909649.03      3162453.05     13910180.49
      3162272.56     13910711.94      3162249.39     13911042.52
#Sta/Elev= 30
  3255.6   57.58  3365.6   57.52  3435.6   56.88  3455.6    57.3  3505.6   56.84
  3515.6   57.12    3814   56.73    3834   57.02    4004   56.44    4034   57.17
  4749.5   56.31  4919.5   56.26  4925.6   56.86  4951.4   48.76    4955   45.39
  4993.3   40.25  4994.8   39.31  4996.2   37.77  4999.3   36.71  5005.2   39.11
    5007   40.62  5058.4   45.25  5085.3   56.42  5170.6   55.97  5230.6   56.29
  5300.6   56.04  5320.6   56.41  5561.9    57.2  5871.9    57.8  5893.3   58.26
#Mann= 3 , 1 , 0
  3255.6     .14       0  4925.6     .04       0  5085.3     .14       0
Bank Sta=4925.6,5085.3
XS Rating Curve= 0
Exp/Cntr=.3,.1

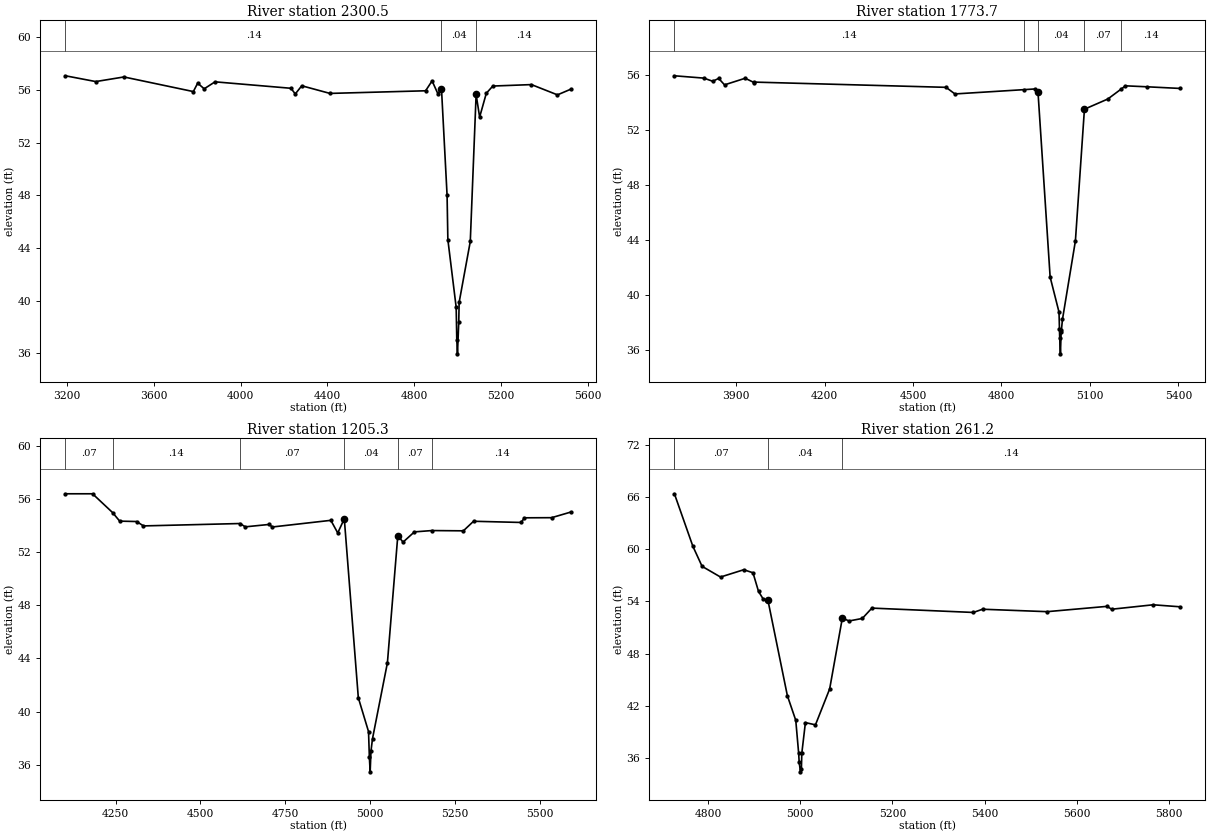
Type RM Length L Ch R = 1 ,2300.5  ,492.3,526.8,544.2
BEGIN DESCRIPTION:
Cross Section 2300.5
END DESCRIPTION:
XS GIS Cut Line= 4
      3163428.46     13909034.51      3162151.52     13909533.22
      3161833.06     13910109.16      3161788.98     13910408.86
#Sta/Elev= 30
  3191.4   57.09  3331.4   56.65  3461.4      57  3781.4   55.89  3801.4   56.53
  3831.4    56.1  3881.4   56.63  4231.4   56.14  4251.4   55.71  4281.4   56.33
  4411.4   55.75  4852.3   55.95  4882.3    56.7  4909.1   55.72  4925.6   56.11
  4951.4   48.01    4955   44.64  4993.3    39.5  4996.2   37.02  4999.3   35.96
  5005.2   38.36    5007   39.87  5058.4    44.5  5085.3   55.67  5101.5   53.95
  5132.3   55.76  5162.3   56.31  5340.4   56.42  5460.4   55.64  5523.3   56.08
#Mann= 3 , 1 , 0
  3191.4     .14       0  4925.6     .04       0  5085.3     .14       0
Bank Sta=4925.6,5085.3
XS Rating Curve= 0
Exp/Cntr=.3,.1

Type RM Length L Ch R = 1 ,1773.7  ,550.7,568.4,601.9
BEGIN DESCRIPTION:
Cross Section 1773.7-Interpolated
END DESCRIPTION:
XS GIS Cut Line= 6
      3162631.67     13908723.51      3161640.83     13909508.65
      3161600.72      13909528.7       3161520.5     13909618.95
      3161420.23     13909759.34       3161368.4     13909859.66
#Sta/Elev= 28
  3690.7   55.93  3790.7   55.76  3820.7   55.53  3840.7   55.74  3860.7   55.27
  3930.7   55.75  3960.7   55.44  3962.1   55.47  4612.1   55.09  4642.1   54.61
  4874.8   54.92  4912.1   54.97  4923.8   54.78  4965.1    41.3  4995.2   38.75
  4996.7   37.52  4997.6   36.85    5000   35.72  5002.4   37.28  5003.3   37.44
  5006.9   38.22  5050.8   43.93  5081.4    53.5  5160.6   54.24  5206.4   54.97
  5220.6    55.2  5293.1   55.13    5406   55.01
#Mann= 5 , 1 , 0
  3690.7     .14       0  4874.8     .07       0  4923.8     .04       0
  5081.4     .07       0  5206.4     .14       0
Bank Sta=4923.8,5081.4
XS Rating Curve= 0
Exp/Cntr=.3,.1

Type RM Length L Ch R = 1 ,1205.3  ,1030.4,944.1,798.5
BEGIN DESCRIPTION:
Cross Section 1205.3
END DESCRIPTION:
XS GIS Cut Line= 4
       3161905.9     13908484.22      3161494.28     13909025.05
      3161169.04     13909133.46      3161148.81     13909600.39
#Sta/Elev= 30
  4102.1    56.4  4182.1    56.4  4240.9   54.99  4262.1   54.34  4312.1   54.31
  4332.1   53.98  4616.7   54.16  4632.1   53.91  4702.1   54.09  4712.1    53.9
  4884.1    54.4  4904.5   53.45  4923.8   54.52  4965.1   41.04  4995.2   38.49
  4997.6   36.59    5000   35.46  5002.4   37.02  5006.9   37.96  5050.8   43.67
  5081.4   53.24    5097   52.76  5130.3   53.53  5181.8   53.63  5274.6   53.61
  5304.6   54.33  5444.6   54.24  5454.6   54.59  5534.6    54.6    5592   55.03
#Mann= 6 , 1 , 0
  4102.1     .07       0  4240.9     .14       0  4616.7     .07       0
  4923.8     .04       0  5081.4     .07       0  5181.8     .14       0
Bank Sta=4923.8,5081.4
XS Rating Curve= 0
Exp/Cntr=.3,.1

Type RM Length L Ch R = 1 ,261.2   ,0,0,0
BEGIN DESCRIPTION:
Cross Section 261.2
END DESCRIPTION:
XS GIS Cut Line= 4
      3160816.71     13908259.39      3160694.75     13908347.48
      3160701.52     13908625.28      3160742.77     13909292.43
#Sta/Elev= 30
  4727.1   66.37  4767.1   60.34  4787.1   58.03  4827.1    56.8  4877.5   57.64
  4897.5   57.29  4909.5   55.15    4920   54.24  4929.9   54.14  4972.1   43.16
  4990.3   40.33  4996.5   36.58  4997.7   35.51  5000.5   34.41  5002.5   34.74
  5003.4   36.55  5011.2   40.07    5033   39.81  5063.8   43.94  5091.3   52.09
  5105.8   51.75  5134.6   52.04  5155.4   53.23  5375.4   52.73  5395.4    53.1
  5535.4   52.82  5665.4   53.43  5675.4    53.1  5765.4   53.61  5823.9   53.38
#Mann= 4 , 1 , 0
  4727.1      .2       0  4727.1     .07       0  4929.9     .04       0
  5091.3     .14       0
Bank Sta=4929.9,5091.3
XS Rating Curve= 0
Exp/Cntr=.3,.1

Chan Stop Cuts=-1